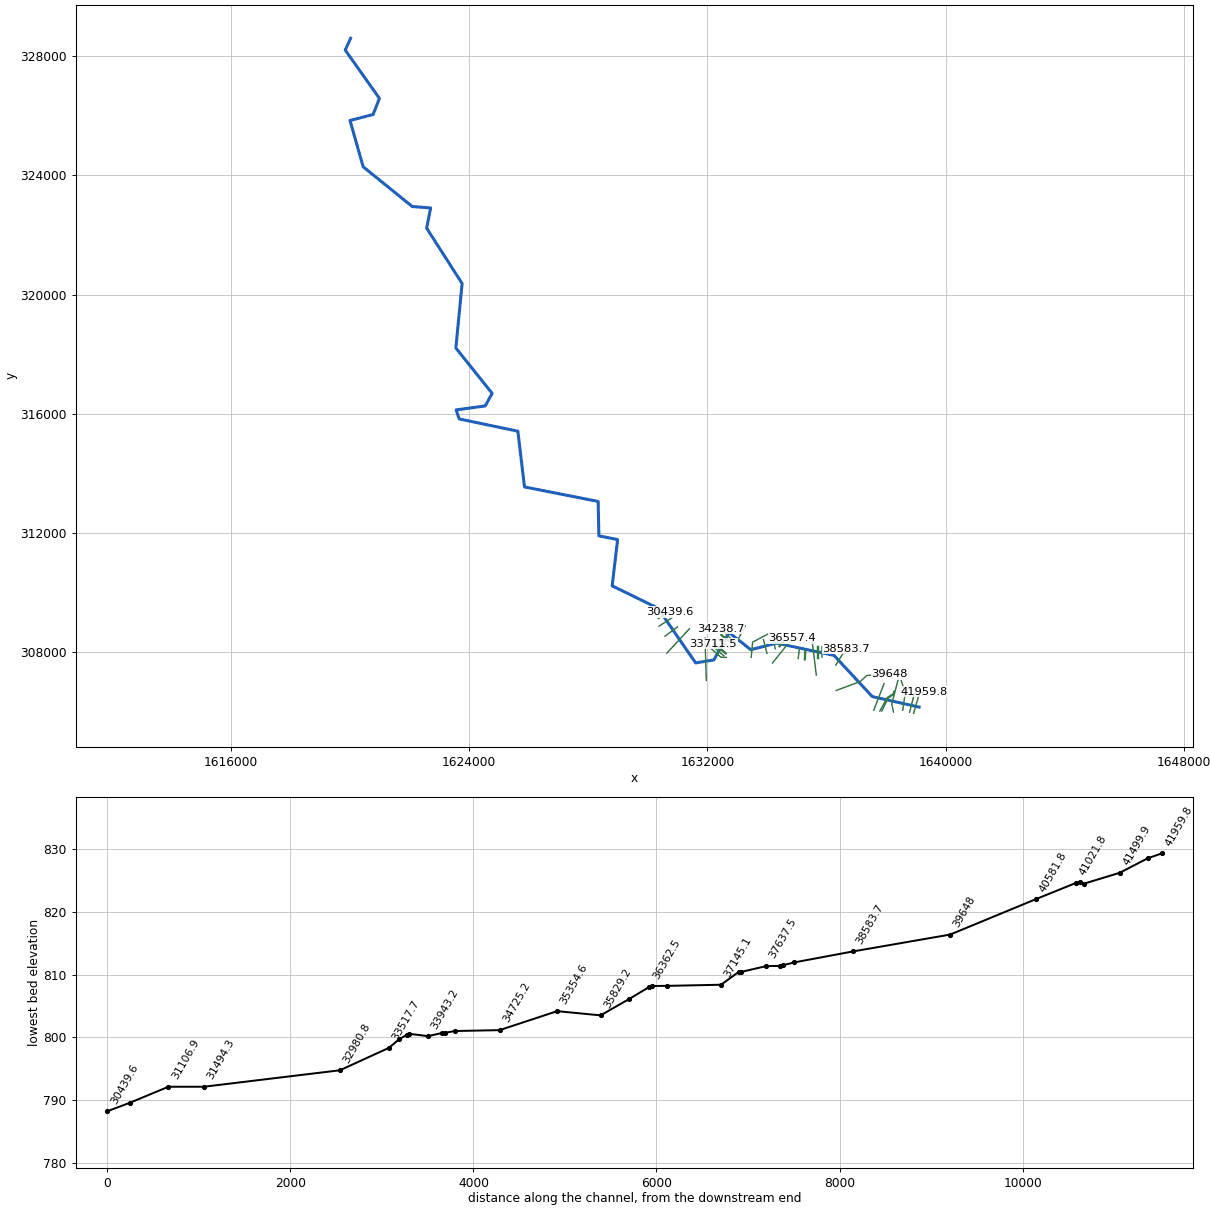
--- FLINTRN.prj (project) ---

Proj Title=FLINTRN
Current Plan=p01
Geom File=g01
Flow File=f01
Plan File=p01
DSS Export Rating Curves=0
DSS Export Rating Curve Sorted=0
DSS Export Volume Flow Curves=0
DXF OffsetX=0
DXF OffsetY=0
DXF ScaleX=0
DXF ScaleY=0

--- FLINTRN.p01 (plan) ---

Plan Title=Floodplain
Program Version=4.00
Geom File=g01
Flow File=f01
K Sum by GR=0
Std Step Tol=0.01
Critical Tol=0.01
Num of Std Step Trials=20
Max Error Tol=0.3
Flow Tol Ratio=0.001
Split Flow NTrial=30
Split Flow Tol=0.02
Split Flow Ratio=0.02
Log Output Level=0
Friction Slope Method=1
Unsteady Friction Slope Method=2
Unsteady Bridges Friction Slope Method=1
Global Log Level=0
CheckData=False
Run HTab=0
Run UNet=0
Run PostProcess=0
UNET Theta=0
UNET Theta Warmup=0
UNET ZTol=0
UNET ZSATol=0
UNET MxIter=0
UNET MaxInSteps=0
UNET DtIC=0
UNET DtMin=0
UNET MaxCRTS=0
UNET WFStab=0
UNET SFStab=0
UNET WFX=0
UNET SFX=0
UNET DSS MLevel=0
UNET DZMax Abort=0
UNET Convert EG Bridges=0
UNET Use Existing IB Tables=0
UNET Froude Limit=0
UNET Froude Power=0
Write IC File=0
Echo Input=False
Echo Output=False
Write Detailed=0

--- FLINTRN.f01 (steady flow) ---

Flow Title=NFF Regression Equation
Program Version=4.10
Number of Profiles= 1
Profile Names=P100yr
River Rch & RM=FLINTRN,Main            ,41959.8
1941.991
River Rch & RM=FLINTRN,Main            ,41499.9
2006.153
River Rch & RM=FLINTRN,Main            ,39648
2205.485
River Rch & RM=FLINTRN,Main            ,38583.7
2323.647
River Rch & RM=FLINTRN,Main            ,34238.7
2503.001
River Rch & RM=FLINTRN,Main            ,26566.8
2717.825
River Rch & RM=FLINTRN,Main            ,22241.7
3019.385
River Rch & RM=FLINTRN,Main            ,21012.1
 3582.31
River Rch & RM=FLINTRN,Main            ,13933.3
3731.049
River Rch & RM=FLINTRN,Main            ,3707.5
4131.478
River Rch & RM=FLINTRN,Main            ,3037.8
4900.632
River Rch & RM=FLINTRN,Main            ,119.5
4955.802
Boundary for River Rch & Prof#=FLINTRN,Main            , 1
Up Type= 0
Dn Type= 3
Dn Slope=0.002117
DSS Import GetInterval= 0
DSS Import GetPeak= 0
DSS Import FillOption= 0

--- FLINTRN.g01 (geometry) ---

Geom Title=USGS 10m DEM
Program Version=4.10

River Reach=FLINTRN         ,Main
Reach XY= 30
     1639102.528      306159.192     1637530.306      306512.665
     1636244.889      307895.998     1634319.422      308305.588
     1633453.103      308085.102     1632724.688      308661.491
     1632214.966      307742.741     1631602.466      307642.741
      1630334.41      309480.935     1628801.772      310228.852
     1628983.849      311780.606     1628356.245      311906.474
     1628330.521      313061.148     1625859.497      313548.153
     1625636.841      315417.944     1623668.959      315830.271
      1623565.66      316133.222     1624542.223      316266.035
     1624773.125      316688.778     1623556.112      318209.611
     1623766.377       320374.49     1622576.186      322231.652
     1622709.519      322910.124     1622092.852      322958.735
     1620444.386      324292.937     1620004.348      325846.011
      1620778.48      326045.247     1620990.285       326588.65
     1619844.061      328207.164     1620022.256      328602.391

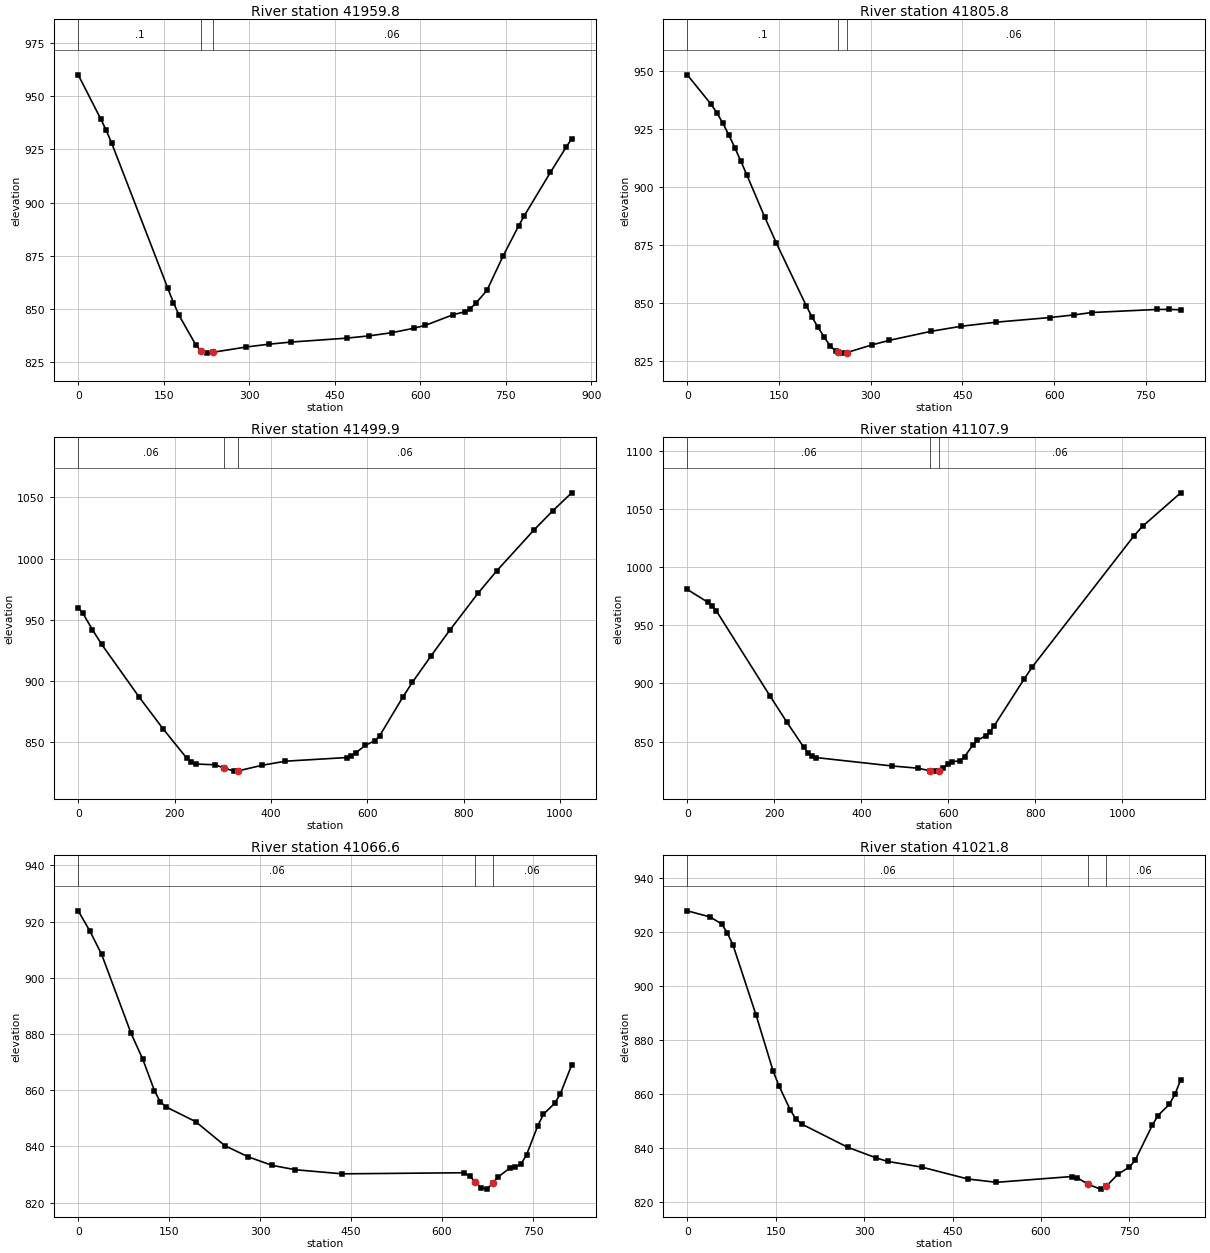
Type RM Length L Ch R = 1 ,41959.8 ,152.8,154,154.8
XS GIS Cut Line= 3
     1638917.248      305948.932     1639117.035      306637.639
     1639260.265      306676.702
#Sta/Elev= 30
       0  960.01    39.3   939.4    49.1  933.96    58.9  927.81   157.2  859.77
     167  853.09   176.8  847.12   206.3  833.21   216.1   830.2   225.9  829.36
   235.8  829.74   294.7  832.23     334  833.54   373.3  834.55   471.5  836.41
   510.8  837.48   550.1  838.95   589.4  841.08     609  842.42   658.2  847.45
   677.8  848.73   687.6  850.25   697.4  852.74   717.1  858.91   744.9  874.73
   772.8  889.23     782  893.64   828.4  914.27   856.3  926.25   865.6  929.98
#Mann= 3 , 0 , 0
       0      .1       0   216.1    .045       0   235.8     .06       0
Bank Sta=216.1,235.8
XS Rating Curve= 0 ,0
Exp/Cntr=0.3,0.1

Type RM Length L Ch R = 1 ,41805.8 ,303.6,305.9,308.2
XS GIS Cut Line= 2
     1638781.972      305986.959     1638985.097      306768.209
#Sta/Elev= 30
       0  948.43    38.9  935.77    48.6     932    58.4  927.51    68.1  922.45
    77.8  917.03    87.5  911.33    97.3  905.39   126.4  887.33   145.9  875.88
   194.5  849.05   204.2  844.06     214  839.64   223.7   835.6   233.4  831.82
   243.1  829.32   246.1  829.09   252.9  828.58   261.1  828.83   301.5  832.08
   330.7   834.1   398.8  837.96   447.4  840.13   505.7  841.92   593.3  843.91
   632.2  845.02   661.3  846.06   768.3  847.39   787.8  847.42   807.2  847.22
#Mann= 3 , 0 , 0
       0      .1       0   246.1    .045       0   261.1     .06       0
Bank Sta=246.1,261.1
XS Rating Curve= 0 ,0
Exp/Cntr=0.3,0.1

Type RM Length L Ch R = 1 ,41499.9 ,394.1,392,389.8
XS GIS Cut Line= 3
     1638552.805      306056.924     1638635.265      306637.639
     1638500.716      307054.306
#Sta/Elev= 30
       0  960.01     9.8  955.21    29.3     942    48.9  929.78   127.1  886.47
     176  860.93   224.8  837.09   234.6  833.41   244.4  832.07   283.5  831.45
     303  828.88   322.6  826.26   331.9  826.46   381.2     831   430.1  834.38
   557.2  837.36     567  838.94   576.8  841.41   596.3  847.37   615.7  851.17
   625.5  854.98   674.1   886.9   693.6  898.79   732.5  920.52   771.4  941.48
   829.8  971.59   868.7  989.93   946.6 1023.62   985.5  1039.2  1024.4 1053.77
#Mann= 3 , 0 , 0
       0     .06       0     303    .045       0   331.9     .06       0
Bank Sta=303,331.9
XS Rating Curve= 0 ,0
Exp/Cntr=0.3,0.1

Type RM Length L Ch R = 1 ,41107.9 ,62.6,41.3,23.1
XS GIS Cut Line= 3
     1638241.952      305992.953      1638184.66      306263.786
     1638401.975      307093.368
#Sta/Elev= 30
       0  981.03    47.7  969.88    57.3  966.88    66.8  962.59   190.9  888.81
   229.1  866.62   267.3  845.35   276.8  840.52   286.6  837.34   296.3   836.2
   471.7  828.92   530.2  827.05   557.1  824.89   569.2  824.52   578.9  824.84
   588.7  827.08   598.4  830.44   608.2  832.38   627.6  833.64   637.4     837
   656.9  847.13   666.6  850.98   686.1     855   695.9  858.44   705.6  863.61
   773.8  903.51   793.3  914.37  1027.2 1027.33  1046.7 1035.43  1134.4 1064.23
#Mann= 3 , 0 , 0
       0     .06       0   557.1    .045       0   578.9     .06       0
Bank Sta=557.1,578.9
XS Rating Curve= 0 ,0
Exp/Cntr=0.3,0.1

Type RM Length L Ch R = 1 ,41066.6 ,67.7,44.8,33.7
XS GIS Cut Line= 4
     1637849.591      306030.135     1638065.534      306463.237
     1638249.331      306581.061     1638277.639      306688.946
#Sta/Elev= 30
       0  923.83    19.4  916.57    38.7   908.3    87.1  880.27   106.5  871.03
   125.8  859.81   135.5  855.82   145.2  854.03   193.6  848.84     242  840.26
   280.7  836.28   319.4  833.29   358.1  831.72   435.6  830.26   635.8  830.65
   645.3  829.47   654.8  827.45   664.3  825.38   673.8  824.82   683.3  826.86
   692.8  829.21   711.6  832.27   720.9   832.6   730.2  833.75   739.4  837.04
     758  847.42   767.3   851.5   785.9  855.37   795.2  858.79   813.8  868.97
#Mann= 3 , 0 , 0
       0     .06       0   654.8    .045       0   683.3     .06       0
Bank Sta=654.8,683.3
XS Rating Curve= 0 ,0
Exp/Cntr=0.3,0.1

Type RM Length L Ch R = 1 ,41021.8 ,399.5,440,465.7
XS GIS Cut Line= 4
     1637784.487      306027.097     1638038.827      306485.575
     1638232.283      306601.706     1638255.938      306685.473
#Sta/Elev= 30
       0  927.69    38.8  925.42    58.3  922.83      68  919.47    77.7  914.92
   116.5  889.22   145.6  868.37   155.4  862.96   174.8   853.9   184.5  850.52
   194.2  848.72   271.9  840.16   320.4   836.2   339.8  834.91   398.1  832.77
   475.8   828.4   524.3  827.16   651.8   829.3   661.6  828.84   680.2  826.38
   700.9  824.64   710.7  825.68   730.3  830.16   749.9   832.8   759.6   835.3
   788.6  848.22   798.3  851.88   817.6  856.01   827.3  859.79     837  865.16
#Mann= 3 , 0 , 0
       0     .06       0   680.2    .045       0   710.7     .06       0
Bank Sta=680.2,710.7
XS Rating Curve= 0 ,0
Exp/Cntr=0.3,0.1

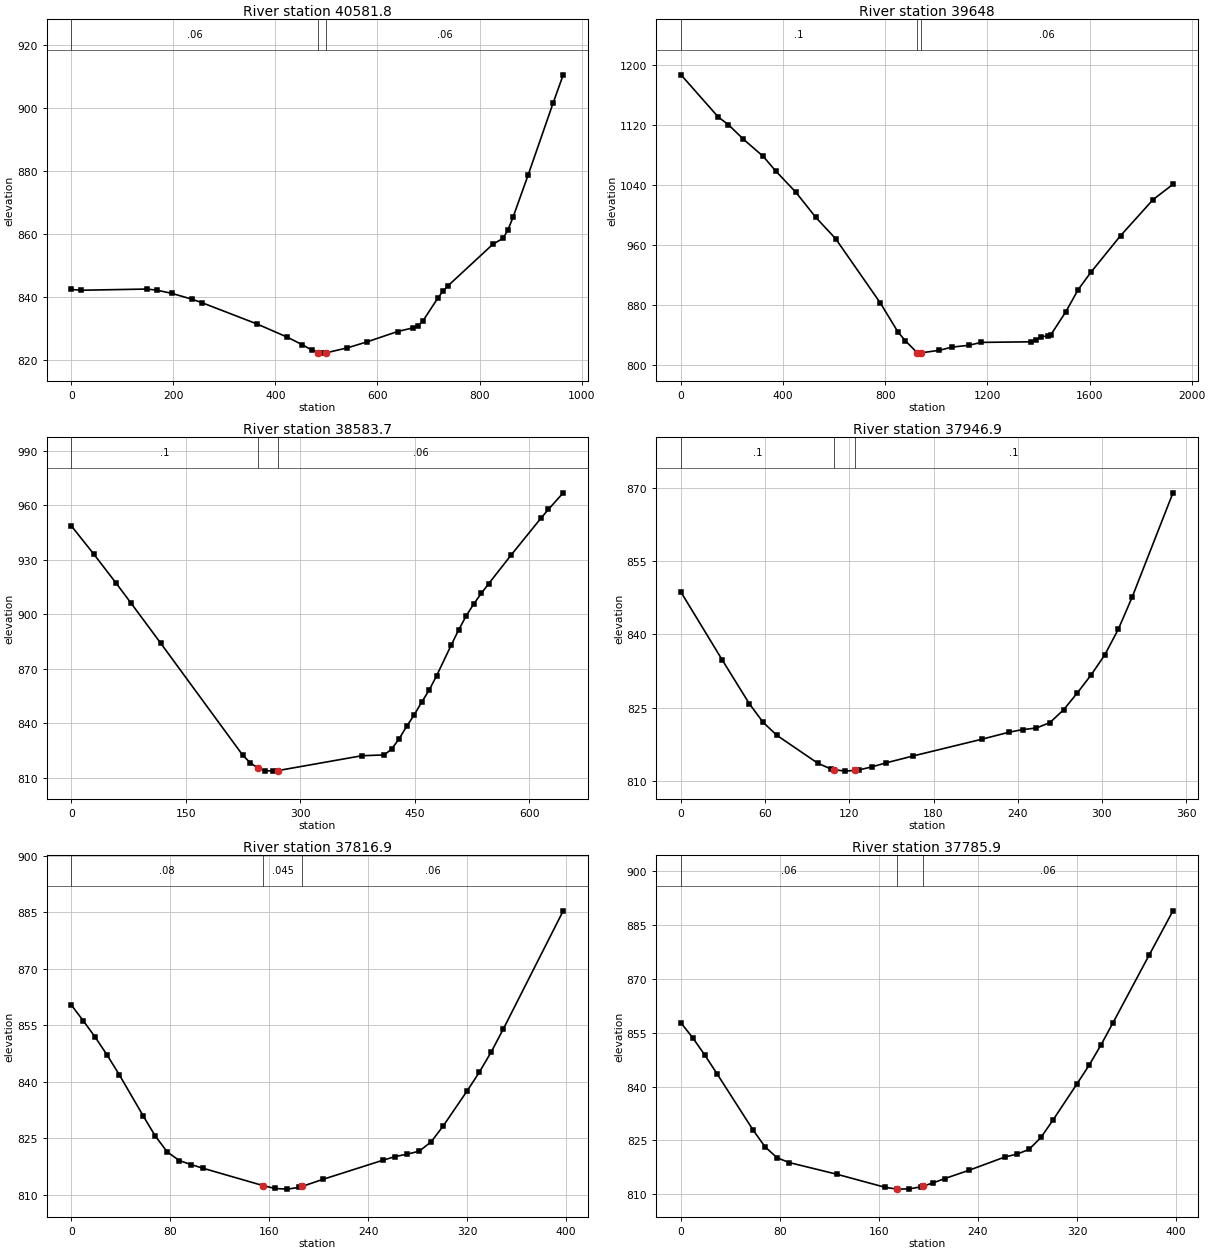
Type RM Length L Ch R = 1 ,40581.8 ,943.5,933.8,923.8
XS GIS Cut Line= 2
     1637578.847      306050.761     1637926.069      306950.067
#Sta/Elev= 30
       0  842.25    19.7  842.01   147.6  842.39   167.2  842.05   196.7  841.03
   236.1  839.19   255.8  838.08     364   831.3     423  827.13   452.5  824.73
   472.2  822.93   483.4  822.23   491.8  822.04   498.4  822.11     541  823.71
   580.4  825.66   639.4   828.9   668.9  830.04   678.7  830.62   688.6  832.14
   718.1  839.47   727.9  841.63   737.8  843.36   826.3  856.64     846  858.48
   855.8   861.2   865.6  865.17   895.2  878.58   944.3  901.52     964  910.42
#Mann= 3 , 0 , 0
       0     .06       0   483.4    .045       0   498.4     .06       0
Bank Sta=483.4,498.4
XS Rating Curve= 0 ,0
Exp/Cntr=0.3,0.1

Type RM Length L Ch R = 1 ,39648   ,1058.3,1064.4,1070.4
XS GIS Cut Line= 4
      1636318.43      306717.428     1637123.986      307016.039
     1637349.388      307223.248     1638110.091      307253.959
#Sta/Elev= 30
       0  1186.4   146.4 1130.09   185.5 1120.19   244.1 1100.89   322.2 1077.86
     371 1058.48   449.1 1030.53   527.2  997.16   605.3  968.62     781  882.85
   849.4  844.64   878.3  832.89   925.7  816.71   935.7   816.4   940.7  816.82
  1012.2  820.15    1060  824.37    1127  826.77    1175  830.68  1370.3  831.44
  1389.8   833.6  1409.3   838.4  1438.6  839.03  1448.4  840.87  1506.9  871.33
  1555.7  900.99  1604.5  923.61  1721.6  972.67  1848.5 1020.44  1926.6  1040.8
#Mann= 3 , 0 , 0
       0      .1       0   925.7    .045       0   940.7     .06       0
Bank Sta=925.7,940.7
XS Rating Curve= 0 ,0
Exp/Cntr=0.3,0.1

Type RM Length L Ch R = 1 ,38583.7 ,622.7,636.8,648.2
XS GIS Cut Line= 2
     1636304.969      307566.893     1636645.681      308113.768
#Sta/Elev= 30
       0  948.71    29.3  933.24    58.6  917.22    78.1  906.26   117.2  884.06
   224.5   822.5   234.3  818.33   244.1  815.48   253.8  814.02   263.6   813.7
   271.1  814.03   380.7  822.18     410  822.61   419.8  825.99   429.6  831.62
   439.3  838.38   449.1  844.63   458.8  851.57   468.6  858.19   478.4  866.12
   497.9  883.32   507.6   891.6   517.4  899.24   527.2  905.75   536.9  911.46
   546.7  916.86     576  932.57     615  952.83   624.8  957.69   644.3  966.85
#Mann= 3 , 0 , 0
       0      .1       0   244.1    .045       0   271.1     .06       0
Bank Sta=244.1,271.1
XS Rating Curve= 0 ,0
Exp/Cntr=0.3,0.1

Type RM Length L Ch R = 1 ,37946.9 ,130,129.9,129.8
XS GIS Cut Line= 2
     1635842.904      307838.651     1635841.168      308189.346
#Sta/Elev= 26
       0  848.65    29.2  834.84    48.7  825.78    58.4  822.01    68.2  819.33
    97.4   813.6   107.2  812.35   109.1  812.27   116.9  811.96   124.1  812.12
   126.6  812.18   136.4  812.86   146.1  813.65   165.6  815.08   214.3  818.49
   233.8  819.94   243.5  820.47   253.3   820.8     263  821.91   272.8  824.56
   282.5  827.99   292.2  831.63     302  835.75   311.7  841.03   321.5  847.56
   350.7  869.02
#Mann= 3 , 0 , 0
       0      .1       0   109.1    .045       0   124.1      .1       0
Bank Sta=109.1,124.1
XS Rating Curve= 0 ,0
Exp/Cntr=0.3,0.1

Type RM Length L Ch R = 1 ,37816.9 ,30.7,31,31.4
XS GIS Cut Line= 2
     1635715.208      307799.896     1635715.208      308197.465
#Sta/Elev= 28
       0  860.35     9.7  856.17    19.4  851.78    29.1  847.01    38.8  841.85
    58.2  830.89    67.9  825.58    77.6  821.35    87.3  819.08      97  817.98
   106.7  817.01   155.2  812.41   164.8  811.66   174.5  811.49   184.2  811.95
   186.7  812.22   203.6  814.11   252.1  819.18   261.8  820.13   271.5  820.77
   281.2  821.56   290.9  824.05   300.6  828.24     320  837.58   329.7  842.46
   339.4  847.88   349.1  853.92   397.6  885.33
#Mann= 3 , 0 , 0
       0     .08       0   155.2    .045       0   186.7     .06       0
Bank Sta=155.2,186.7
XS Rating Curve= 0 ,0
Exp/Cntr=0.3,0.1

Type RM Length L Ch R = 1 ,37785.9 ,145.2,148.4,151.7
XS GIS Cut Line= 2
     1635685.694      307799.896     1635685.694      308197.465
#Sta/Elev= 28
       0  857.75     9.7   853.5    19.4   848.7    29.1  843.57    58.2   827.9
    67.9   823.2    77.6  820.16    87.3  818.82   126.1  815.54   164.8  811.92
   174.5   811.4   184.2  811.45   193.9  812.04   195.9  812.26   203.6  813.12
   213.3  814.36   232.7  816.65   261.8  820.37   271.5  821.16   281.2  822.46
   290.9  825.81   300.6  830.65     320  840.74   329.7  845.88   339.4   851.6
   349.1  857.77   378.2  876.57   397.6  889.01
#Mann= 3 , 0 , 0
       0     .06       0   174.5    .045       0   195.9     .06       0
Bank Sta=174.5,195.9
XS Rating Curve= 0 ,0
Exp/Cntr=0.3,0.1

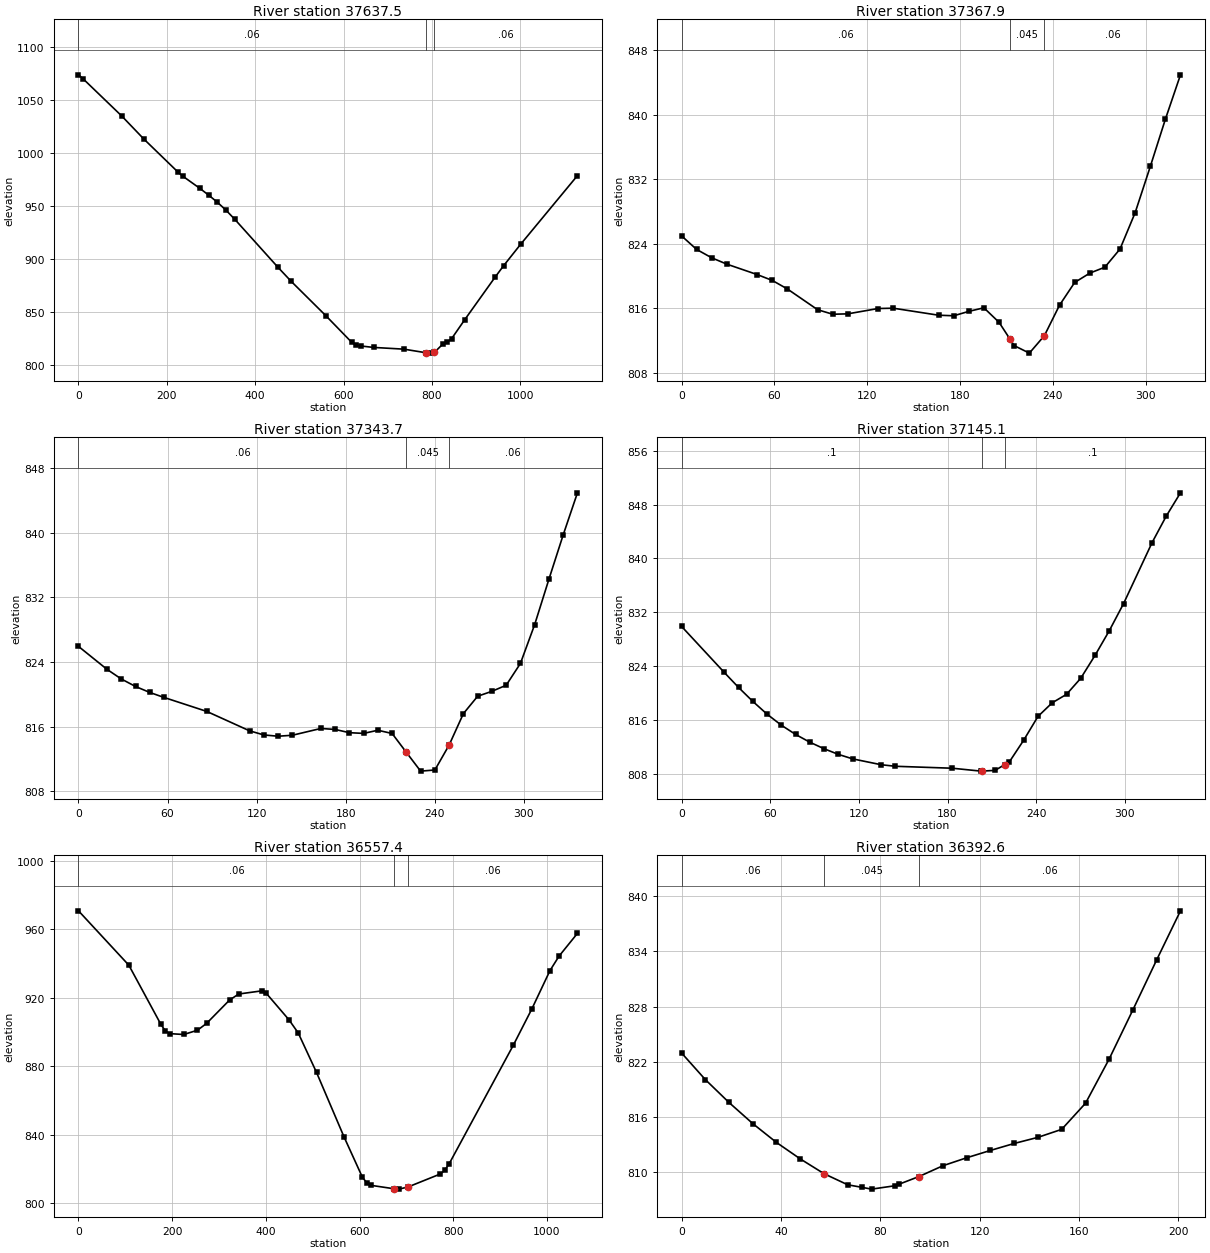
Type RM Length L Ch R = 1 ,37637.5 ,273.5,269.5,265.5
XS GIS Cut Line= 2
     1635652.639      307232.348     1635515.039      308353.351
#Sta/Elev= 30
       0 1073.52     9.8 1070.02    98.2 1034.61   147.3  1013.3   225.9  981.63
   235.7  978.16     275  966.48   294.6   960.2   314.3   953.5   333.9     946
   353.6   937.5   451.8  892.09   481.2  879.08   559.8  846.66   618.7  821.43
   628.5  818.95   638.4  818.12   667.8  816.74   736.6   815.1   785.7  811.78
   795.5  811.36   805.8  812.13     825  820.02   834.8  821.71   844.6     825
   874.1  842.74   942.8   882.8   962.5  893.82  1001.7  914.34  1129.4  978.58
#Mann= 3 , 0 , 0
       0     .06       0   785.7    .045       0   805.8     .06       0
Bank Sta=785.7,805.8
XS Rating Curve= 0 ,0
Exp/Cntr=0.3,0.1

Type RM Length L Ch R = 1 ,37367.9 ,24.4,24.3,24.1
XS GIS Cut Line= 2
     1635279.444       307756.84     1635297.194       308078.97
#Sta/Elev= 30
       0  824.99     9.8   823.3    19.6  822.26    29.3  821.48    48.9  820.19
    58.7  819.46    68.4  818.41      88  815.83    97.8  815.27   107.5  815.32
   127.1  815.98   136.9  816.02   166.2  815.15     176  815.08   185.8  815.63
   195.5  816.07   205.3  814.27   212.2  812.24   215.1  811.38   224.9  810.45
   234.6  812.61   244.4  816.39   254.2  819.21     264  820.37   273.7   821.1
   283.5  823.35   293.3  827.86   303.1  833.59   312.8  839.42   322.6  844.95
#Mann= 3 , 0 , 0
       0     .06       0   212.2    .045       0   234.6     .06       0
Bank Sta=212.2,234.6
XS Rating Curve= 0 ,0
Exp/Cntr=0.3,0.1

Type RM Length L Ch R = 1 ,37343.7 ,200,198.6,197.1
XS GIS Cut Line= 2
     1635253.402      307744.688      1635273.54      308080.055
#Sta/Elev= 30
       0  825.94    19.2   823.1    28.8  821.91    38.4  820.98      48  820.24
    57.6  819.62    86.4  817.89   115.2  815.49   124.8  814.98   134.4  814.82
     144  814.94   163.2  815.78   172.8  815.66   182.4  815.26     192  815.17
   201.6  815.56   211.2  815.16   220.8  812.82   230.4   810.5     240  810.64
   249.6  813.73   259.2  817.62   268.8  819.77   278.4  820.38     288  821.13
   297.6  823.83   307.2  828.64   316.8  834.26   326.4  839.74     336  844.95
#Mann= 3 , 0 , 0
       0     .06       0   220.8    .045       0   249.6     .06       0
Bank Sta=220.8,249.6
XS Rating Curve= 0 ,0
Exp/Cntr=0.3,0.1

Type RM Length L Ch R = 1 ,37145.1 ,599.6,587.7,575.8
XS GIS Cut Line= 2
     1635044.293      307786.568     1635085.959      308121.637
#Sta/Elev= 30
       0   829.9    28.9  823.06    38.6  820.82    48.2  818.76    57.9  816.85
    67.5  815.22    77.2  813.84    86.8  812.69    96.5  811.71   106.1  810.88
   115.8  810.21   135.1  809.34   144.7  809.11   183.3  808.82   202.6  808.39
   203.6   808.4   212.2   808.5   218.6  809.35   221.9  809.79   231.5  812.98
   241.2  816.52   250.8  818.54   260.5   819.8   270.1  822.18   279.8  825.59
   289.4  829.24   299.1  833.28   318.4  842.35     328  846.29   337.6  849.74
#Mann= 3 , 0 , 0
       0      .1       0   203.6    .045       0   218.6      .1       0
Bank Sta=203.6,218.6
XS Rating Curve= 0 ,0
Exp/Cntr=0.3,0.1

Type RM Length L Ch R = 1 ,36557.4 ,163.1,164.8,166.4
XS GIS Cut Line= 2
     1634180.996      307636.935     1634845.348      308469.327
#Sta/Elev= 30
       0  970.71   107.5  938.95   175.9   904.4   185.6  900.47   195.4  898.99
   224.7   898.5     254     901   273.6  905.03   322.4   918.6     342  922.14
   390.8  923.96   400.6  922.63   449.4  907.04     469  899.41   508.1  876.35
   566.7  838.77   605.8  815.27   615.6  811.75   625.3  810.38   674.2   808.4
     684  808.21   703.5  809.48   771.9     817   781.7  819.17   791.4  823.11
   928.2  892.28   967.3  913.21  1006.4  935.83  1025.9  944.32    1065  957.55
#Mann= 3 , 0 , 0
       0     .06       0   674.2    .045       0   703.5     .06       0
Bank Sta=674.2,703.5
XS Rating Curve= 0 ,0
Exp/Cntr=0.3,0.1

Type RM Length L Ch R = 1 ,36392.6 ,30,30.1,30.1
XS GIS Cut Line= 2
     1634425.711      308182.188     1634537.691      308348.854
#Sta/Elev= 24
       0  822.98     9.6  820.08    19.1   817.6    28.7   815.3    38.2  813.26
    47.8  811.47    57.4  809.86    66.9  808.66    72.5  808.39    76.5  808.19
      86  808.56    87.5  808.72    95.6  809.56   105.2  810.73   114.7  811.59
   124.3  812.39   133.9  813.15   143.4  813.81     153  814.68   162.6  817.52
   172.1  822.32   181.7  827.68   191.2  833.07   200.8  838.41
#Mann= 3 , 0 , 0
       0     .06       0    57.4    .045       0    95.6     .06       0
Bank Sta=57.4,95.6
XS Rating Curve= 0 ,0
Exp/Cntr=0.3,0.1

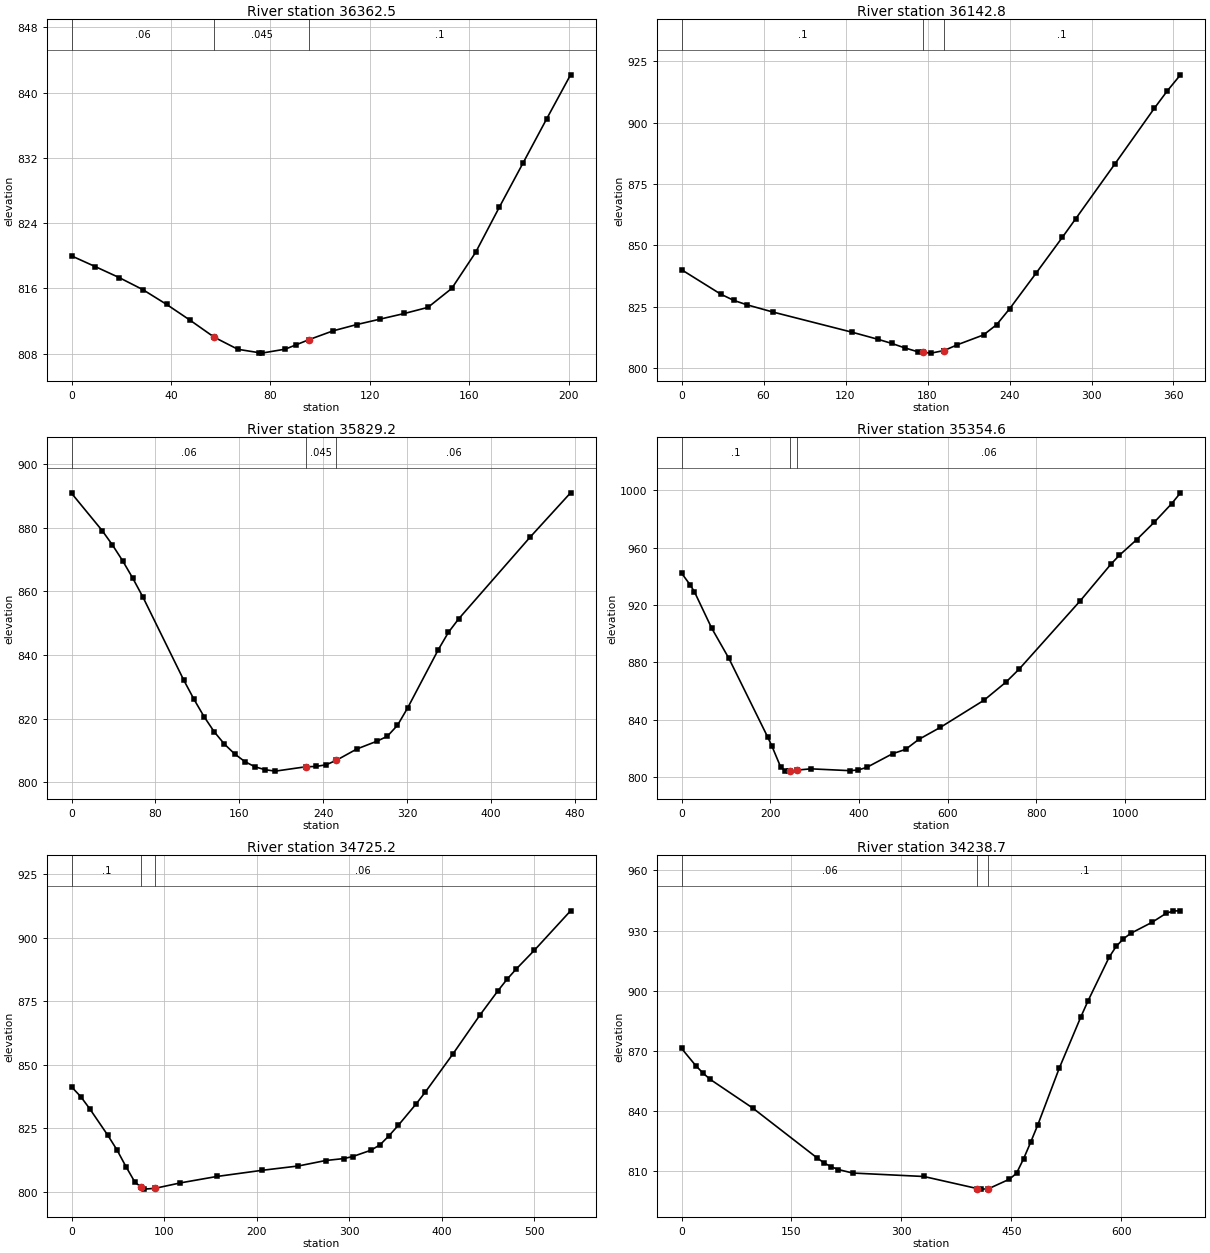
Type RM Length L Ch R = 1 ,36362.5 ,201,219.7,238
XS GIS Cut Line= 2
     1634399.529      308196.968     1634511.508      308363.635
#Sta/Elev= 24
       0  819.97     9.6  818.65    19.1  817.32    28.7  815.83    38.2  814.03
    47.8  812.06    57.4     810    66.9  808.52    75.5   808.1    76.5  808.05
      86  808.54    90.5  809.09    95.6  809.71   105.2  810.78   114.7  811.55
   124.3  812.23   133.9  812.91   143.4  813.66     153  815.99   162.6  820.41
   172.1  825.93   181.7  831.38   191.2  836.79   200.8  842.18
#Mann= 3 , 0 , 0
       0     .06       0    57.4    .045       0    95.6      .1       0
Bank Sta=57.4,95.6
XS Rating Curve= 0 ,0
Exp/Cntr=0.3,0.1

Type RM Length L Ch R = 1 ,36142.8 ,313.1,313.6,314
XS GIS Cut Line= 2
     1634275.196      308116.429     1634193.598      308472.332
#Sta/Elev= 25
       0  840.13    28.8  830.13    38.4  827.58      48   825.8    67.3  822.81
   124.9  814.64   144.1  811.71   153.7  810.11   163.4  808.26     173  806.67
   176.8  806.46   182.6  806.13   191.8  807.15   192.2  807.19   201.8  809.53
     221  813.55   230.6  817.74   240.2  824.28   259.4  838.68   278.7  853.34
   288.3  860.78   317.1  883.21   345.9  905.84   355.5  913.02   365.1  919.53
#Mann= 3 , 0 , 0
       0      .1       0   176.8    .045       0   191.8      .1       0
Bank Sta=176.8,191.8
XS Rating Curve= 0 ,0
Exp/Cntr=0.3,0.1

Type RM Length L Ch R = 1 ,35829.2 ,482.2,474.6,466.8
XS GIS Cut Line= 2
     1633996.389      307961.515     1633880.924      308423.229
#Sta/Elev= 30
       0  890.81    29.1  879.13    38.8  874.66    48.6  869.66    58.3  864.17
      68  858.22   106.8  832.21   116.6  826.14   126.3  820.64     136  815.87
   145.7  812.01   155.4  808.94   165.1  806.52   174.8  804.87   184.6  803.94
   194.3   803.5   223.4  804.87   233.1  804.97   242.8   805.5   252.5   806.9
     272  810.45   291.4  812.93   301.1  814.45   310.8   817.9   320.5  823.36
   349.7  841.65   359.4  847.12   369.1  851.33   437.1  876.97   475.9  890.98
#Mann= 3 , 0 , 0
       0     .06       0   223.4    .045       0   252.5     .06       0
Bank Sta=223.4,252.5
XS Rating Curve= 0 ,0
Exp/Cntr=0.3,0.1

Type RM Length L Ch R = 1 ,35354.6 ,638.4,629.4,620.4
XS GIS Cut Line= 3
     1633467.744      307828.702     1633516.489      308341.304
     1634056.285      308625.577
#Sta/Elev= 30
       0  942.22    19.4  934.03    29.2  929.12      68  903.84   106.9  882.71
   194.3  827.92     204  821.48   223.4  807.13   233.2  804.46   242.9  804.17
   245.7  804.27   260.7   804.9   291.5  805.77   378.9   804.5   398.3  804.96
   417.8   806.8     476  816.33   505.2  819.31   534.6  826.22   583.8   834.7
   682.2  853.63   731.4  866.17   760.9  875.15   898.7  922.78   967.6  948.21
   987.2  954.62  1026.6  965.62    1066  977.69  1105.3  990.66    1125  998.16
#Mann= 3 , 0 , 0
       0      .1       0   245.7    .045       0   260.7     .06       0
Bank Sta=245.7,260.7
XS Rating Curve= 0 ,0
Exp/Cntr=0.3,0.1

Type RM Length L Ch R = 1 ,34725.2 ,456.8,486.4,516
XS GIS Cut Line= 2
     1633012.014      308406.827     1633264.619       308883.39
#Sta/Elev= 30
       0  841.33     9.8  837.55    19.6  832.74    39.2  822.28      49  816.59
    58.8  809.96    68.6  803.77    75.1  802.03    78.4  801.14    90.1  801.45
   117.7   803.6   156.9  806.11   205.9  808.54   245.2  810.25   274.6  812.39
   294.2  813.16     304  813.96   323.6  816.44   333.4  818.56   343.2  822.17
     353  826.17   372.7  834.76   382.5  839.37   411.9  854.14   441.3  869.54
   460.9  879.15   470.7  883.67   480.5  887.65   500.1  895.02   539.4   910.6
#Mann= 3 , 0 , 0
       0      .1       0    75.1    .045       0    90.1     .06       0
Bank Sta=75.1,90.1
XS Rating Curve= 0 ,0
Exp/Cntr=0.3,0.1

Type RM Length L Ch R = 1 ,34238.7 ,106.9,109.3,111.8
XS GIS Cut Line= 2
     1632930.403      308310.382      1632446.91       308789.64
#Sta/Elev= 30
       0  871.21    19.4  862.63    29.2  858.94    38.9  855.81    97.2  841.44
   184.8  816.63   194.5  814.07   204.2  812.16     214  810.77   233.4  809.03
   330.7   807.3   403.4  801.29   408.5     801   418.4  801.12   447.4  805.95
   457.1  808.92   466.8  816.18   476.5  824.49   486.3  833.21   515.4  861.33
   544.6  886.69   554.3  894.64   583.5  916.72   593.2  922.16     603  925.88
   612.7  928.56   641.9  934.09   661.3   938.6     671  939.78   680.8  939.84
#Mann= 3 , 0 , 0
       0     .06       0   403.4    .045       0   418.4      .1       0
Bank Sta=403.4,418.4
XS Rating Curve= 0 ,0
Exp/Cntr=0.3,0.1

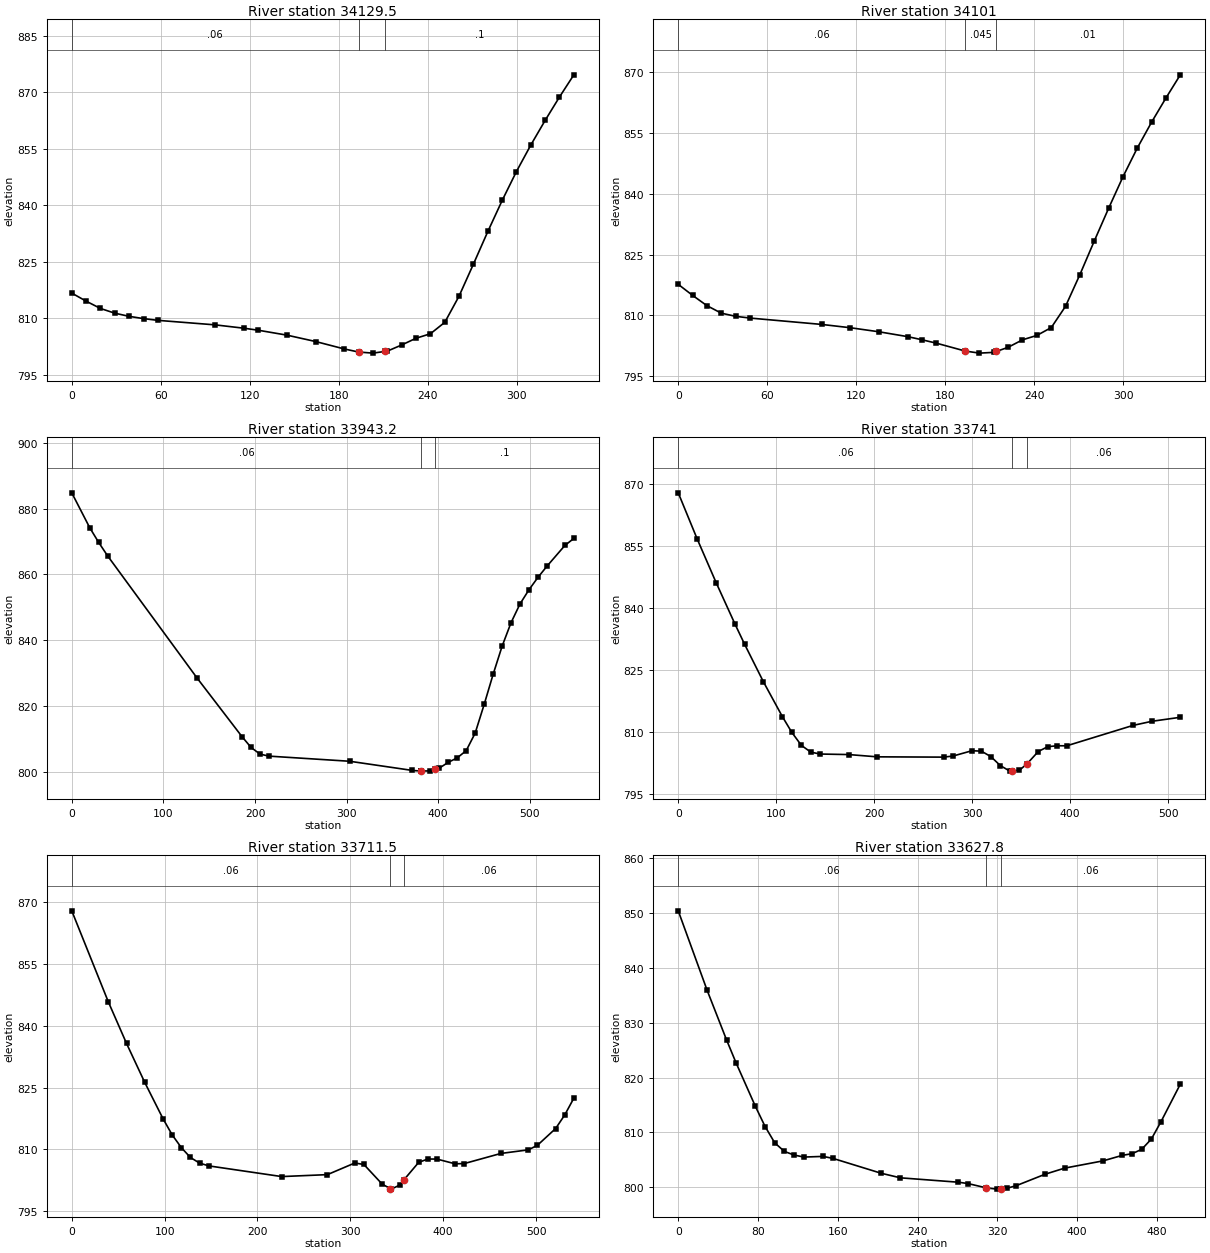
Type RM Length L Ch R = 1 ,34129.5 ,28.5,28.5,28.5
XS GIS Cut Line= 2
     1632730.312      308387.005     1632465.555      308597.943
#Sta/Elev= 30
       0  816.65     9.7  814.51    19.3  812.58      29  811.32    38.7  810.48
    48.4  809.88      58  809.42    96.7  808.22   116.1  807.33   125.7   806.8
   145.1  805.49   164.4   803.8   183.8  801.82   193.4  801.01   203.1  800.72
   211.3  801.18   212.8  801.26   222.4  802.88   232.1  804.67   241.8  805.86
   251.5   808.9   261.1  815.84   270.8  824.35   280.5     833   290.2  841.26
   299.8  848.92   309.5  855.96   319.2  862.52   328.8  868.69   338.5  874.58
#Mann= 3 , 0 , 0
       0     .06       0   193.4    .045       0   211.3      .1       0
Bank Sta=193.4,211.3
XS Rating Curve= 0 ,0
Exp/Cntr=0.3,0.1

Type RM Length L Ch R = 1 ,34101   ,156.8,157.8,158.7
XS GIS Cut Line= 2
     1632716.857      308361.398       1632452.1      308572.335
#Sta/Elev= 29
       0  817.67     9.7  814.94    19.3  812.42      29  810.56    38.7  809.78
    48.4  809.35    96.7  807.78   116.1  806.96   135.4  805.96   154.8  804.76
   164.4  803.99   174.1  803.15   193.4  801.22   203.1   800.7   212.8  800.89
   214.5  801.11   222.4  802.14   232.1  803.98   241.8  805.07   251.5     807
   261.1  812.24   270.8  820.07   280.5  828.36   290.2  836.46   299.8  844.17
   309.5   851.3   319.2  857.71   328.8  863.63   338.5  869.35
#Mann= 3 , 0 , 0
       0     .06       0   193.4    .045       0   214.5     .01       0
Bank Sta=193.4,214.5
XS Rating Curve= 0 ,0
Exp/Cntr=0.3,0.1

Type RM Length L Ch R = 1 ,33943.2 ,203.1,202.2,201.1
XS GIS Cut Line= 2
     1632782.493      308129.349     1632339.784      308452.266
#Sta/Elev= 30
       0   884.8    19.6   874.2    29.4  869.71    39.1  865.64     137   828.4
   185.9  810.63   195.7  807.38   205.5  805.35   215.3  804.74   303.3  803.18
   371.8  800.39   381.3  800.19   381.6  800.18   391.4  800.27   396.3  800.69
   401.2  801.11     411  802.86   420.8  804.23   430.5  806.41   440.3  811.74
   450.1  820.44   459.9  829.62   469.7  838.17   479.5  845.35   489.2     851
     499  855.32   508.8  859.09   518.6  862.47   538.2  868.79     548  870.94
#Mann= 3 , 0 , 0
       0     .06       0   381.3    .045       0   396.3      .1       0
Bank Sta=381.3,396.3
XS Rating Curve= 0 ,0
Exp/Cntr=0.3,0.1

Type RM Length L Ch R = 1 ,33741   ,29.6,29.5,29.4
XS GIS Cut Line= 2
     1632629.419      307972.076      1632229.05      308292.045
#Sta/Elev= 30
       0  867.95    19.3   856.8    38.7  846.19      58  836.13    67.7   831.3
      87  822.16   106.4  813.71     116  809.91   125.7  806.79   135.4  805.14
     145  804.69   174.1  804.56   203.1  804.01   270.8  803.94   280.4   804.2
   299.8  805.49   309.4  805.39   319.1  804.07   328.8  801.89   338.5  800.55
   341.1   800.6   348.1  800.74   356.1  802.33   367.5   805.3   377.1  806.46
   386.8   806.7   396.5  806.68   464.2  811.62   483.5  812.62   512.5  813.59
#Mann= 3 , 0 , 0
       0     .06       0   341.1    .045       0   356.1     .06       0
Bank Sta=341.1,356.1
XS Rating Curve= 0 ,0
Exp/Cntr=0.3,0.1

Type RM Length L Ch R = 1 ,33711.5 ,85.6,83.7,81.9
XS GIS Cut Line= 2
      1632615.53      307944.299     1632194.328      308283.365
#Sta/Elev= 30
       0  867.79    39.3  845.78      59  835.66    78.6  826.23    98.3  817.43
   108.1  813.54     118  810.44   127.8  808.05   137.6   806.7   147.5  806.02
   226.1  803.43   275.3   803.9   304.8  806.72   314.6  806.36   334.3   801.6
   342.9  800.54   344.1  800.39   353.9  801.45   357.9  802.69   373.6  806.87
   383.4  807.68   393.2  807.67   412.9  806.52   422.7  806.58   462.1  809.03
   491.6   809.9   501.4  810.99   521.1  815.07   530.9  818.36   540.7  822.42
#Mann= 3 , 0 , 0
       0     .06       0   342.9    .045       0   357.9     .06       0
Bank Sta=342.9,357.9
XS Rating Curve= 0 ,0
Exp/Cntr=0.3,0.1

Type RM Length L Ch R = 1 ,33627.8 ,109.8,110.1,110.4
XS GIS Cut Line= 2
     1632552.111      307875.312     1632175.592      308209.514
#Sta/Elev= 30
       0  850.37      29  835.88    48.4  826.88    58.1  822.63    77.4  814.74
    87.1  811.08    96.8   808.1   106.5  806.54   116.2  805.89   125.9  805.52
   145.2  805.64   154.9  805.29   203.3  802.58   222.7  801.74   280.8  800.94
   290.4   800.7   308.8  799.91   319.5  799.68   323.8  799.74   329.2  799.82
   338.9  800.31   367.9   802.4   387.3   803.5     426  804.83   445.4  805.84
     455  806.13   464.7  806.93   474.4  808.81   484.1  811.99   503.4   818.8
#Mann= 3 , 0 , 0
       0     .06       0   308.8    .045       0   323.8     .06       0
Bank Sta=308.8,323.8
XS Rating Curve= 0 ,0
Exp/Cntr=0.3,0.1

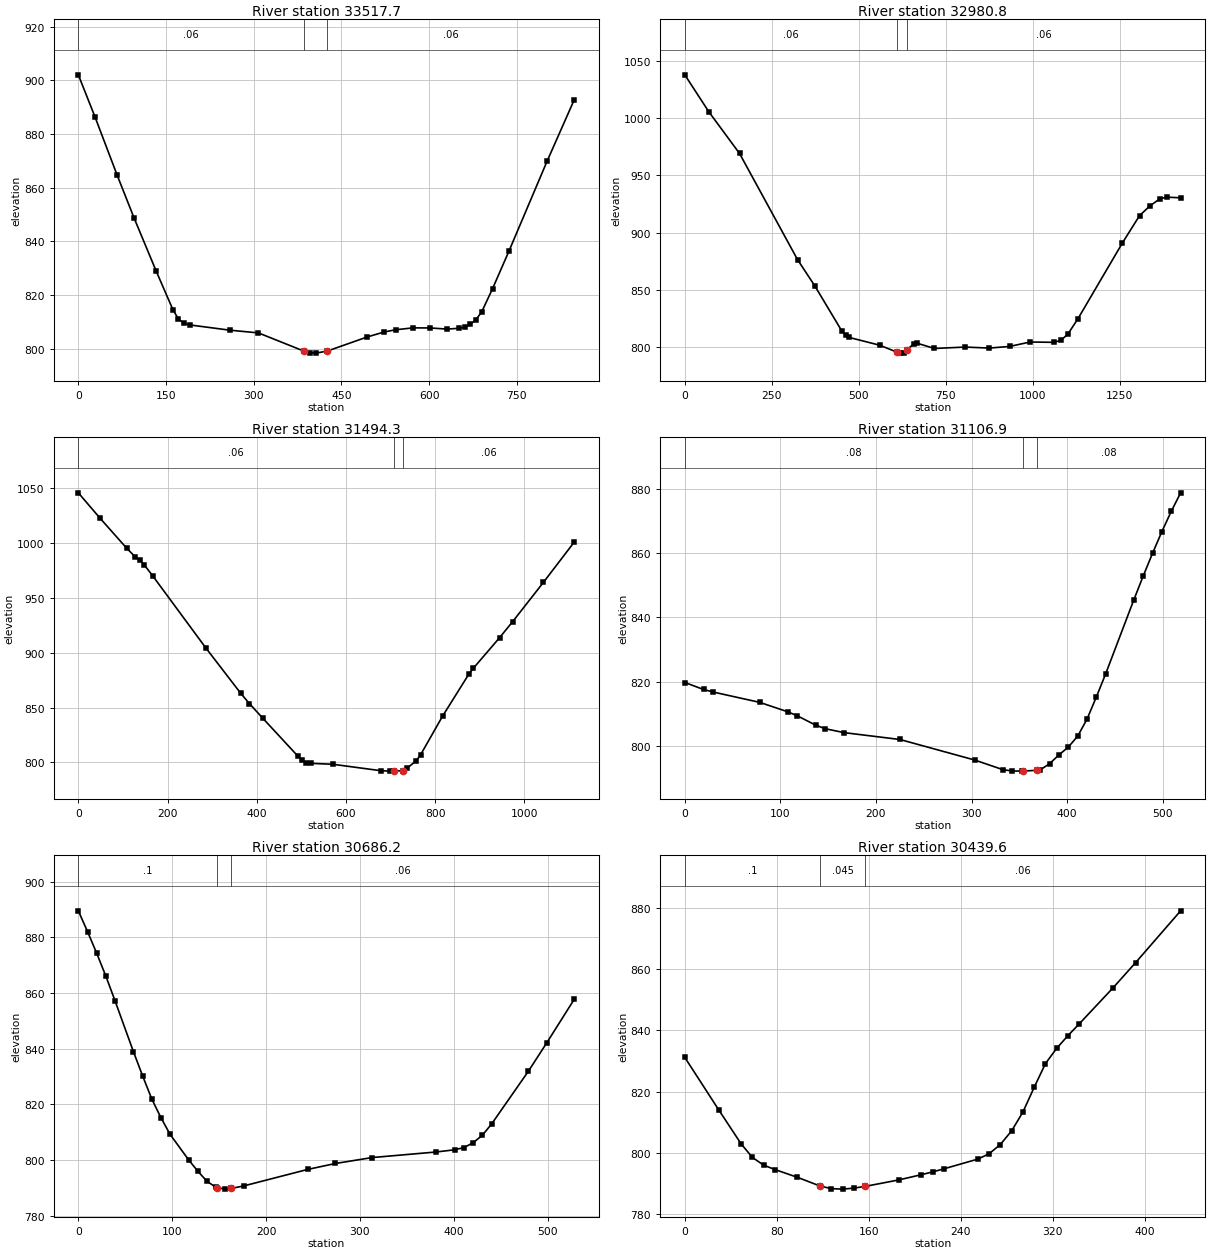
Type RM Length L Ch R = 1 ,33517.7 ,555.5,536.9,518.4
XS GIS Cut Line= 4
     1632631.962      307825.455     1632451.407      307832.399
     1632069.462      308169.205     1632045.157      308325.455
#Sta/Elev= 30
       0   902.1    28.5  886.41    66.6  864.56    95.1  848.85   133.1  828.93
   161.7  814.56   171.2  811.03   180.7  809.44   190.5  808.84     259  806.88
     308  805.86   386.3  799.03   395.9  798.47   405.9  798.32   425.5  799.07
   494.1  804.35   523.4  806.23     543  807.04   572.4  807.74   601.8  807.71
   631.2  807.27   650.8   807.6   660.5  807.97   670.3  809.03   680.1  810.82
   689.9  813.71   708.5  822.39   736.4  836.32   801.5   869.8     848  892.74
#Mann= 3 , 0 , 0
       0     .06       0   386.3    .045       0   425.5     .06       0
Bank Sta=386.3,425.5
XS Rating Curve= 0 ,0
Exp/Cntr=0.3,0.1

Type RM Length L Ch R = 1 ,32980.8 ,1502.5,1486.4,1469.7
XS GIS Cut Line= 2
     1631960.785      307055.174     1631917.383      308478.785
#Sta/Elev= 30
       0 1037.89    68.8  1005.7   157.2  969.21   324.1  876.29   373.3  853.57
   451.8  813.68   461.7  810.21   471.5  808.48   559.9  801.66     609  795.63
   618.8  794.73   628.6  795.22   638.9  797.87   658.1  802.95   667.9  803.34
     717   798.8   805.4  800.03   874.2  799.14   933.1  800.58   992.1  804.45
  1060.8  804.16  1080.5  805.99  1100.1   811.2  1129.6   824.9  1257.3  891.13
  1306.4   914.9  1335.9  923.33  1365.3   929.7    1385     931  1424.3  930.43
#Mann= 3 , 0 , 0
       0     .06       0     609    .045       0   638.9     .06       0
Bank Sta=609,638.9
XS Rating Curve= 0 ,0
Exp/Cntr=0.3,0.1

Type RM Length L Ch R = 1 ,31494.3 ,392.4,387.4,382.7
XS GIS Cut Line= 2
     1630638.737      307970.973     1631393.945      308786.945
#Sta/Elev= 30
       0 1045.55    49.2 1022.19   108.2  995.22   127.9  987.08   137.8  984.08
   147.6  980.05   167.3  969.65   285.3  904.62     364  863.05   383.7  853.56
   413.2  840.46     492  805.88   501.8  802.03   511.6  799.81   521.5  799.18
   570.7  798.34   678.9  792.46   698.6   792.1   708.4   792.1   728.1  792.64
   737.9     795   757.6  801.54   767.4  806.95   816.6  842.09   875.7  880.46
   885.5  885.66   944.6  913.65   974.1  928.36    1043  964.08  1111.8 1000.62
#Mann= 3 , 0 , 0
       0     .06       0   708.4    .045       0   728.1     .06       0
Bank Sta=708.4,728.1
XS Rating Curve= 0 ,0
Exp/Cntr=0.3,0.1

Type RM Length L Ch R = 1 ,31106.9 ,422.2,420.7,418.7
XS GIS Cut Line= 2
     1630576.127      308541.617     1630992.794      308850.645
#Sta/Elev= 30
       0   819.7    19.6  817.53    29.4  816.75    78.3  813.52   107.7  810.58
   117.4  809.38     137  806.41   146.8  805.32   166.4   804.1   225.1  801.95
   303.4  795.55   332.8  792.56   342.6  792.14   352.4   792.1   353.4   792.1
   368.4  792.36   371.9  792.49   381.7  794.42   391.5  797.16   401.3  799.59
   411.1     803   420.9  808.32   430.7  815.25   440.4  822.43   469.8  845.42
   479.6  852.83   489.4  859.93   499.2  866.71     509     873   518.8  878.77
#Mann= 3 , 0 , 0
       0     .08       0   353.4    .045       0   368.4     .08       0
Bank Sta=353.4,368.4
XS Rating Curve= 0 ,0
Exp/Cntr=0.3,0.1

Type RM Length L Ch R = 1 ,30686.2 ,247,246.6,245.7
XS GIS Cut Line= 2
     1630374.738      308874.951     1630817.446      309163.145
#Sta/Elev= 30
       0   889.5     9.8  882.04    19.6  874.24    29.4  865.98    39.1  857.18
    58.7  838.91    68.5   830.2    78.3  821.88      88  815.19    97.8  809.18
   117.4   800.1   127.2  796.02     137  792.36   146.7  790.17   147.8   790.1
   156.5  789.54   162.8  789.78   176.1  790.68   244.6  796.64   273.9  798.75
     313  800.88   381.5  802.89   401.1  803.68   410.9  804.48   420.6  806.21
   430.4  808.89   440.2  812.91   479.3  831.82   498.9  842.03   528.2  857.68
#Mann= 3 , 0 , 0
       0      .1       0   147.8    .045       0   162.8     .06       0
Bank Sta=147.8,162.8
XS Rating Curve= 0 ,0
Exp/Cntr=0.3,0.1

Type RM Length L Ch R = 1 ,30439.6 ,757,766.9,777.1
XS GIS Cut Line= 2
     1630348.169      309131.104     1630717.961      309353.326
#Sta/Elev= 29
       0  831.16    29.4  814.12      49  802.96    58.8  798.54    68.6  796.01
    78.4  794.58      98  792.04   117.7   789.2   127.5  788.35   137.3  788.19
   147.1  788.52   156.9  789.08   186.3   791.2   205.9  792.91   215.7  793.81
   225.5  794.82   254.9  797.98   264.7  799.71   274.5  802.73   284.4  807.22
   294.2  813.36     304  821.41   313.8  829.15   323.6  834.15   333.4  838.28
   343.2  842.11   372.6  853.86   392.2  862.07   431.4  878.98
#Mann= 3 , 0 , 0
       0      .1       0   117.7    .045       0   156.9     .06       0
Bank Sta=117.7,156.9
XS Rating Curve= 0 ,0
Exp/Cntr=0.3,0.1