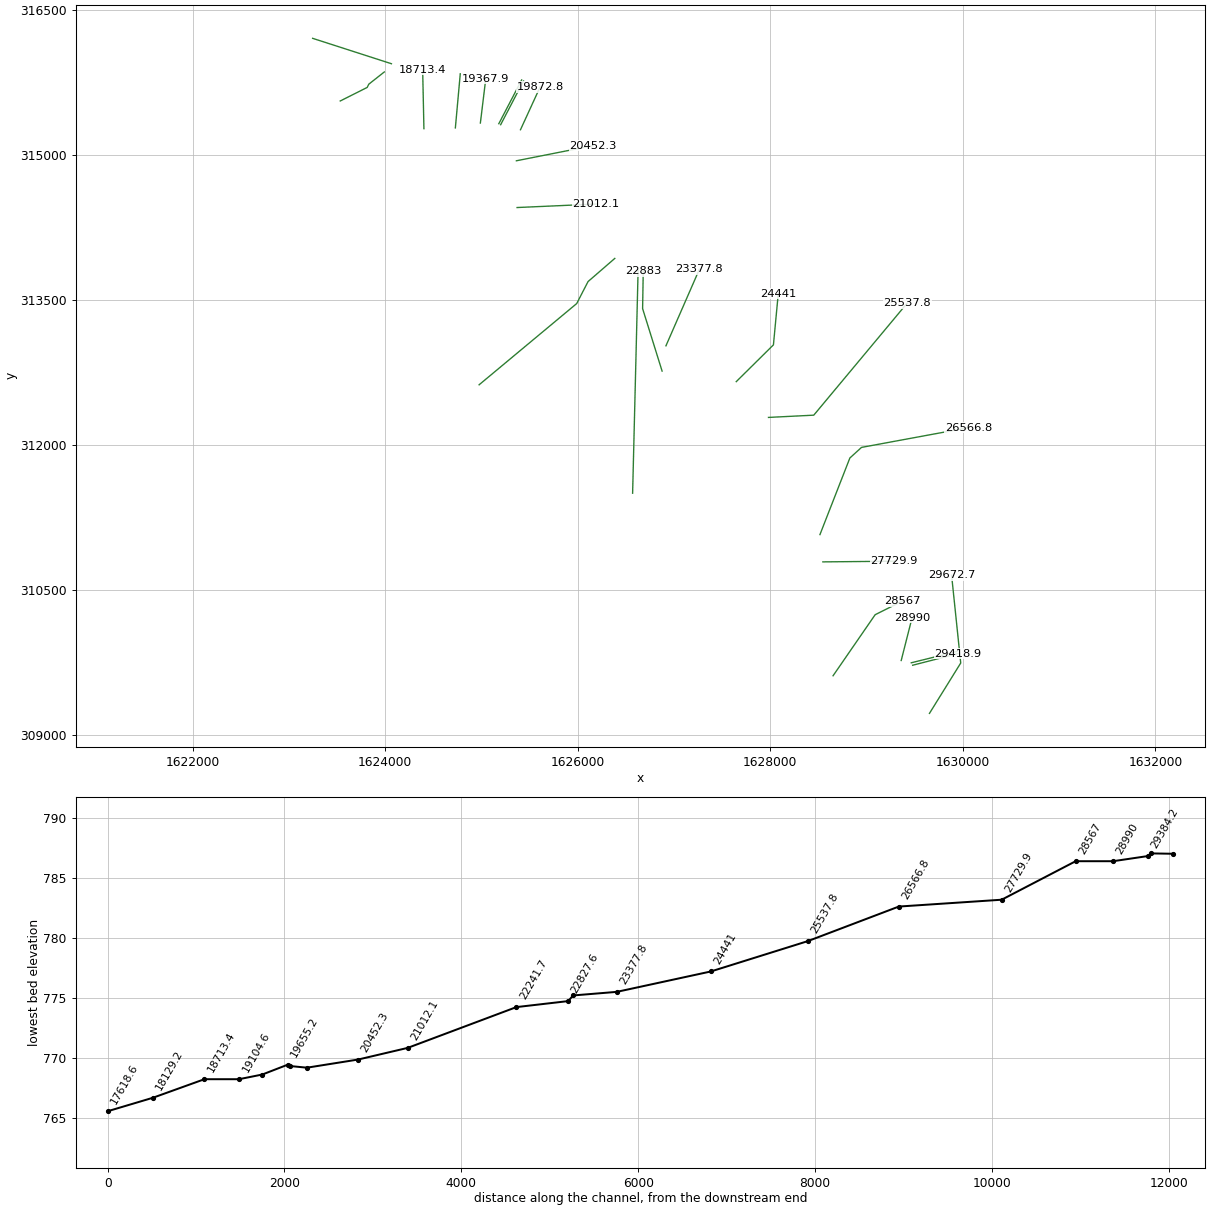
HEC-RAS study FLINTRN.prj: FLINTRN

--- FLINTRN.g01 (geometry) --- (continued)

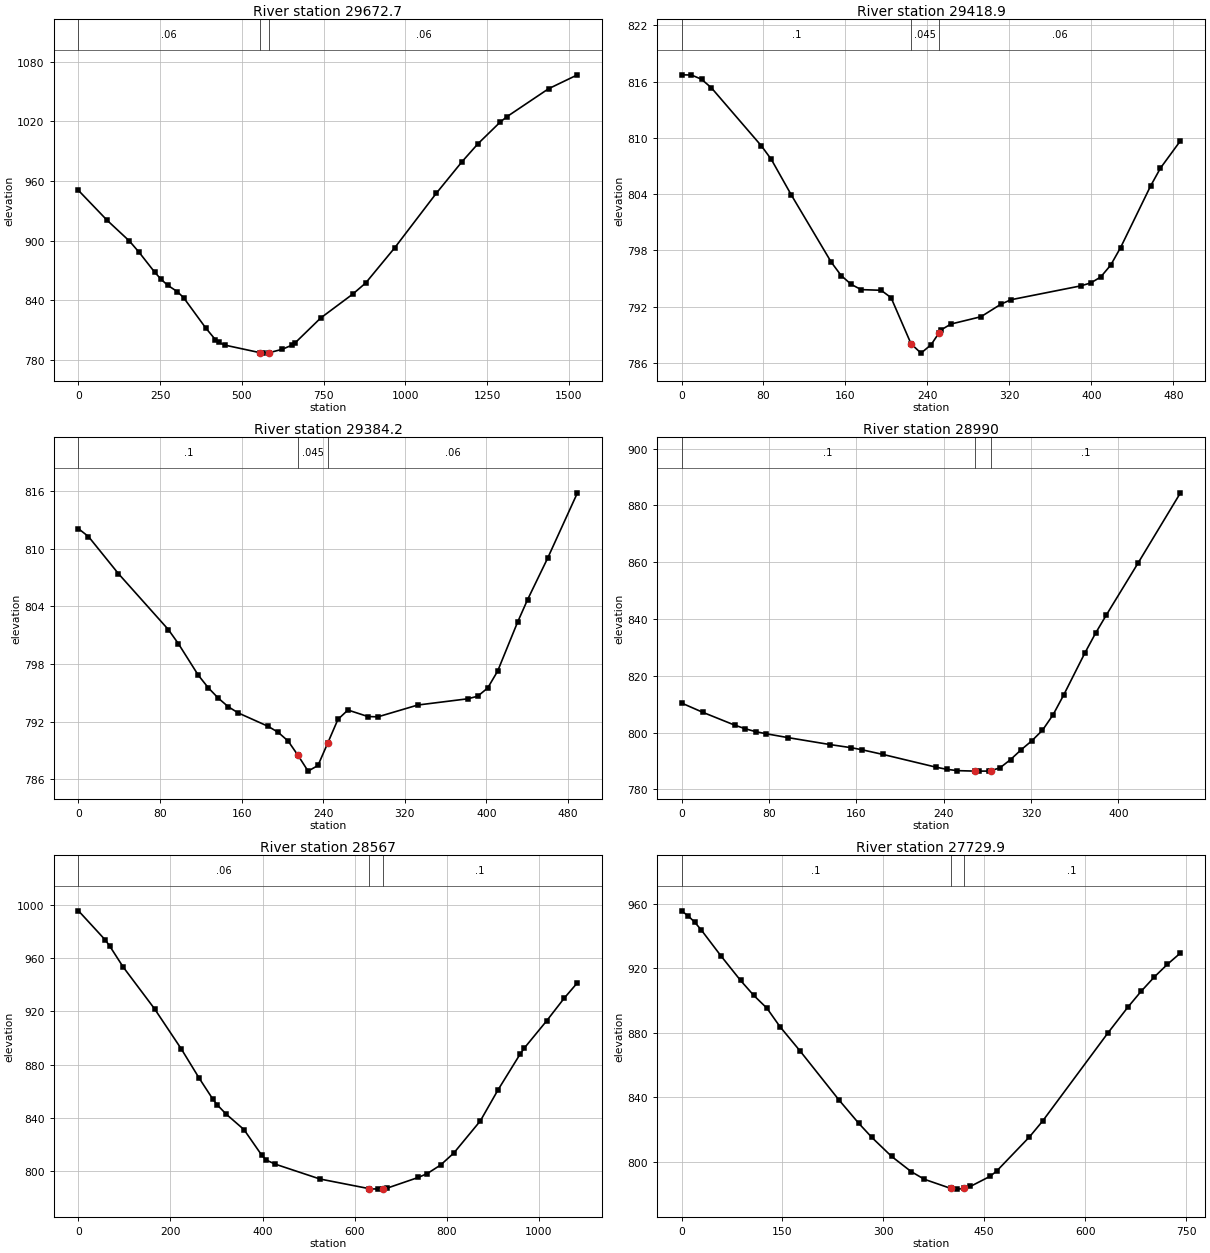
Type RM Length L Ch R = 1 ,29672.7 ,275.4,253.8,231.2
XS GIS Cut Line= 3
     1629653.724      309227.632     1629978.377      309748.465
     1629883.528      310656.736
#Sta/Elev= 30
       0  950.53    87.7   920.5   155.9  899.67   185.1  888.52   233.8  868.11
   253.3  861.08   272.8  855.25     302  848.95   321.5  842.85   389.7  812.16
   418.9  800.61   428.6  797.81   448.1  795.07   555.3  787.48     565  787.02
   584.5  787.54   623.6  790.88     653  795.01   662.8  797.29   741.4  822.39
   839.6  846.42   878.9  857.53   967.2  892.67  1094.9  947.65  1173.4  979.31
  1222.5  997.46  1291.3 1019.47  1310.9 1024.61  1438.6 1052.76  1526.9 1066.73
#Mann= 3 , 0 , 0
       0     .06       0   555.3    .045       0   584.5     .06       0
Bank Sta=555.3,584.5
XS Rating Curve= 0 ,0
Exp/Cntr=0.3,0.1

Type RM Length L Ch R = 1 ,29418.9 ,31.6,34.7,38.5
XS GIS Cut Line= 2
     1629479.172      309725.518     1629950.873      309846.351
#Sta/Elev= 30
       0  816.72     9.7   816.7    19.5  816.25    29.2  815.33    77.9  809.15
    87.6  807.71   107.1  803.92   146.1  796.75   155.8  795.32   165.6  794.38
   175.3  793.82   194.8  793.75   204.5  792.96     224  788.04   233.7  787.05
   243.5  787.94     251  789.16   253.2  789.52   262.9  790.15   292.2  790.93
   311.6  792.26   321.4  792.74   389.6  794.22   399.3  794.53     409  795.16
   418.8  796.43   428.5  798.31   457.7  804.86   467.4  806.78   486.9  809.69
#Mann= 3 , 0 , 0
       0      .1       0     224    .045       0     251     .06       0
Bank Sta=224,251
XS Rating Curve= 0 ,0
Exp/Cntr=0.3,0.1

Type RM Length L Ch R = 1 ,29384.2 ,367.6,394.3,421
XS GIS Cut Line= 2
     1629464.497      309750.856     1629939.671      309868.218
#Sta/Elev= 30
       0   812.1     9.8  811.28    39.2  807.41    88.1  801.59    97.9  800.13
   117.5  796.83   127.3  795.52     137  794.45   146.8  793.55   156.6   792.9
     186   791.5   195.8  790.88   205.6  789.97   215.4  788.46   225.2  786.83
   234.9  787.42   244.7  789.81   254.5  792.23   264.3   793.2   283.9  792.52
   293.7  792.49   332.8  793.72   381.8  794.37   391.6  794.64   401.4   795.5
   411.1  797.25   430.7  802.36   440.5  804.71   460.1  809.01   489.4  815.84
#Mann= 3 , 0 , 0
       0      .1       0   215.4    .045       0   244.7     .06       0
Bank Sta=215.4,244.7
XS Rating Curve= 0 ,0
Exp/Cntr=0.3,0.1

Type RM Length L Ch R = 1 ,28990   ,431.4,423,414.7
XS GIS Cut Line= 2
     1629360.265      309774.415     1629473.112      310217.124
#Sta/Elev= 30
       0   810.4    19.4  807.14    48.6  802.62    58.3  801.34      68   800.3
    77.8  799.55    97.2  798.23   136.1  795.75   155.5  794.65   165.2  793.93
   184.7  792.26   233.3  787.77     243  787.03   252.7  786.57   268.4  786.41
   272.2   786.4   281.9  786.42   283.4  786.59   291.6  787.55   301.3  790.47
   311.1  793.96   320.8  797.09   330.5  800.79   340.2  806.23   349.9  813.18
   369.4  828.06   379.1  834.96   388.8  841.27     418  859.67   456.9  884.46
#Mann= 3 , 0 , 0
       0      .1       0   268.4    .045       0   283.4      .1       0
Bank Sta=268.4,283.4
XS Rating Curve= 0 ,0
Exp/Cntr=0.3,0.1

Type RM Length L Ch R = 1 ,28567   ,858.8,837.1,814.8
XS GIS Cut Line= 3
     1628652.626      309616.806     1629089.705      310248.248
     1629373.112      310389.375
#Sta/Elev= 30
       0  995.48    58.3  973.56      68  968.96    97.2  953.23   165.3  921.88
   223.6  891.66   262.5  869.67   291.6  854.24   301.4  849.76   320.8  842.82
   359.7  831.15   398.6  811.76   408.3  808.21   427.7  805.16   524.9     794
   631.9  786.75   651.3   786.4     661   786.5   670.8  787.14   738.8   795.2
   758.2   798.1   787.1   804.5   815.9  813.53   873.5  837.65   911.9  860.92
   959.8  887.72   969.4  892.48  1017.4  912.71  1055.8  929.84  1084.6  941.45
#Mann= 3 , 0 , 0
       0     .06       0   631.9    .045       0     661      .1       0
Bank Sta=631.9,661
XS Rating Curve= 0 ,0
Exp/Cntr=0.3,0.1

Type RM Length L Ch R = 1 ,27729.9 ,1146.2,1163.1,1179.5
XS GIS Cut Line= 2
     1628546.723      310794.757      1629288.49      310801.634
#Sta/Elev= 30
       0  955.64     9.8  952.52    19.5  948.65    29.3  943.82    58.6  927.73
    87.8  912.49   107.4  903.23   126.9  895.35   146.4  883.84   175.7  869.09
   234.2  838.38   263.5  823.97     283  815.21   312.3  803.48   341.6     794
   361.1  789.28   400.2  783.65   409.9  783.19   419.7  783.58   429.5  784.87
   458.7  791.12   468.5  794.36   517.3  815.55   536.8  825.34   634.4  880.22
   663.7  895.99   683.2  905.71   702.8   914.6   722.3  922.48   741.8   929.5
#Mann= 3 , 0 , 0
       0      .1       0   400.2    .045       0   419.7      .1       0
Bank Sta=400.2,419.7
XS Rating Curve= 0 ,0
Exp/Cntr=0.3,0.1

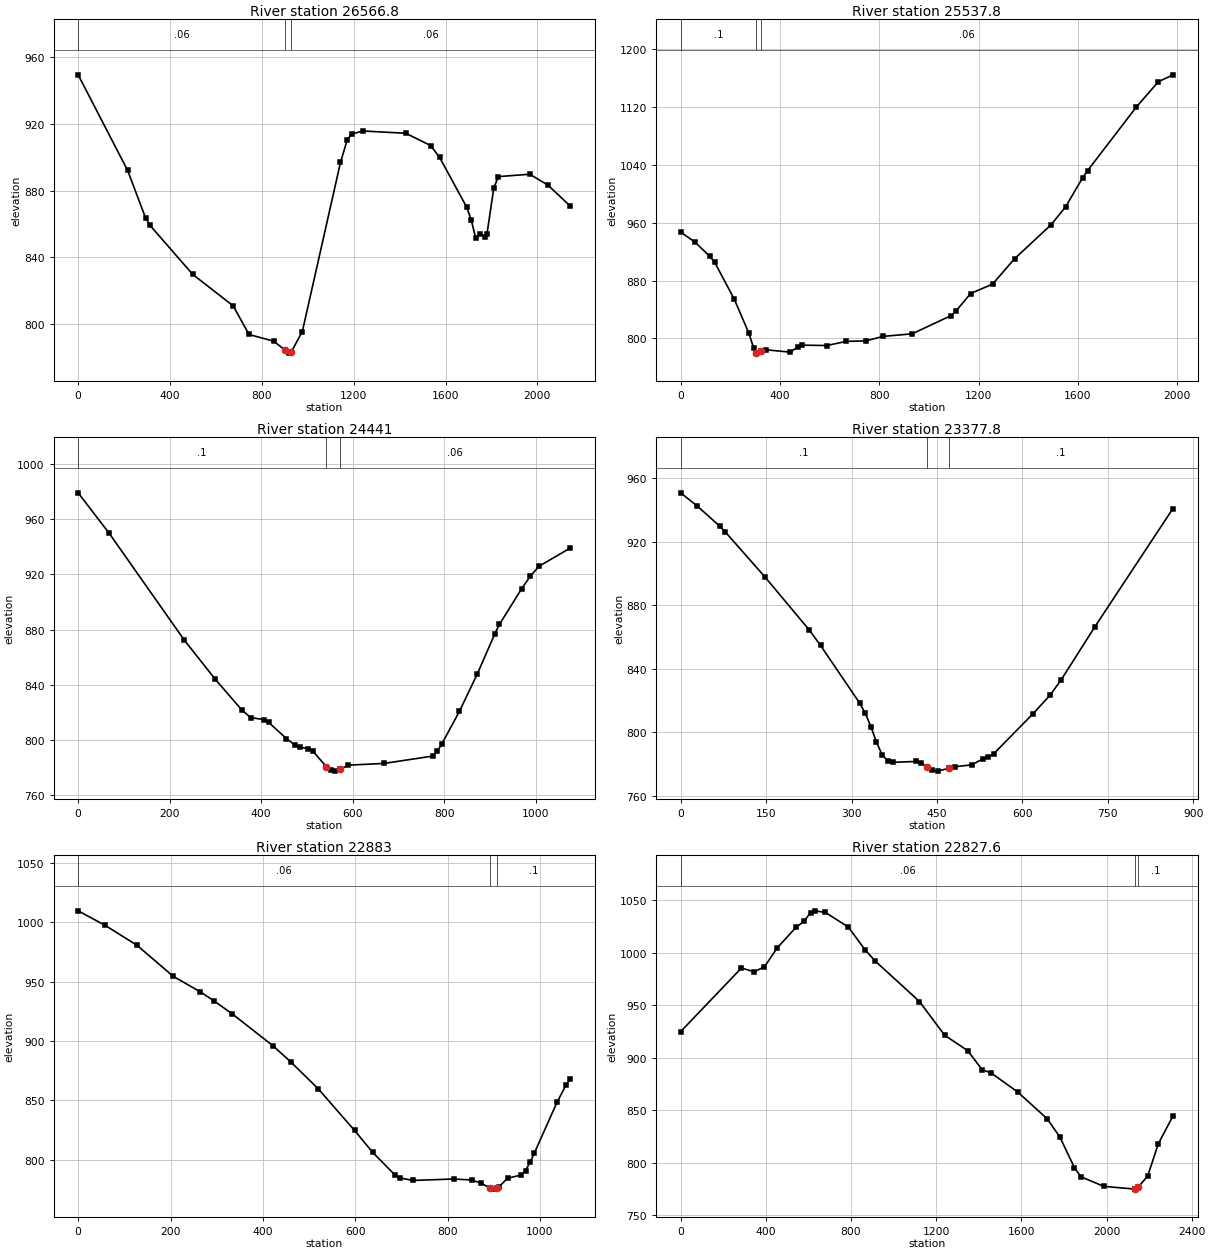
Type RM Length L Ch R = 1 ,26566.8 ,1046.8,1029,1012.2
XS GIS Cut Line= 4
     1628516.185      311076.626     1628827.119      311869.342
     1628948.069      311978.945     1630058.478       312183.12
#Sta/Elev= 30
       0  949.29   215.3  892.08   293.6  863.62   313.2  859.09   499.2  829.73
   675.3  810.91   743.8   793.8   851.5  789.77   899.5  784.61   918.7  782.62
   928.3  783.35   976.3  795.57  1142.4   896.8  1171.8  910.34  1191.4  913.84
  1240.5  915.66  1427.1  914.28  1535.1  906.93  1574.3   899.8  1692.2     870
  1711.8  862.41  1731.4  851.53  1751.1   854.1  1770.7  852.27  1780.5  854.01
    1810   881.4  1829.6  888.33    1967  889.75  2045.6  883.27  2143.8  870.61
#Mann= 3 , 0 , 0
       0     .06       0   899.5    .045       0   928.3     .06       0
Bank Sta=899.5,928.3
XS Rating Curve= 0 ,0
Exp/Cntr=0.3,0.1

Type RM Length L Ch R = 1 ,25537.8 ,1070.8,1096.8,1130
XS GIS Cut Line= 3
     1627981.853      312289.079     1628452.166      312312.304
     1629422.667       313471.57
#Sta/Elev= 30
       0  947.21    58.9  932.95   117.7  913.47   137.3  905.18   215.8  854.43
   274.7  807.19   294.3  786.55   304.1  779.74   323.7  782.56   343.4   784.4
   441.5  781.06   470.9  788.27   490.5  790.76   588.7  790.25   667.2  796.02
   745.8  796.66   814.5  802.87   932.3  806.46  1089.4   831.7    1109  837.97
  1167.9  862.22  1256.3  875.26  1344.6  910.25  1491.9  957.33  1550.8  982.35
  1619.5 1022.69  1639.2 1032.39  1835.5  1120.3  1923.9 1155.18  1982.8 1164.78
#Mann= 3 , 0 , 0
       0      .1       0   304.1    .045       0   323.7     .06       0
Bank Sta=304.1,323.7
XS Rating Curve= 0 ,0
Exp/Cntr=0.3,0.1

Type RM Length L Ch R = 1 ,24441   ,1061.1,1063.3,1057.5
XS GIS Cut Line= 3
       1627647.2      312659.167     1628033.242        313039.6
     1628083.589       313570.85
#Sta/Elev= 30
       0  979.24    67.8  949.87   232.3  872.16     300  843.73   358.1  821.41
   377.5  816.01   406.5  814.62   416.2  812.63   454.9  800.88   474.2  796.03
   483.9  794.56   503.3  793.59     513  791.64     542  780.56   551.7  777.79
   561.4  777.21   571.1   778.4   590.5  781.55   668.1  782.79   774.8  788.14
   784.6  791.53   794.3  796.74   833.1   820.6   871.9   847.6   910.7  877.07
   920.4  883.66   968.9  909.55   988.3  918.87  1007.7  926.08  1075.6  939.22
#Mann= 3 , 0 , 0
       0      .1       0     542    .045       0   571.1     .06       0
Bank Sta=542,571.1
XS Rating Curve= 0 ,0
Exp/Cntr=0.3,0.1

Type RM Length L Ch R = 1 ,23377.8 ,486.4,494.7,501.6
XS GIS Cut Line= 2
     1626916.992      313029.653     1627264.214       313821.32
#Sta/Elev= 30
       0  950.96    29.5  942.49    68.8  929.87    78.6  926.19   147.4  898.16
   225.9  864.45   245.6  854.74   314.4  818.37   324.2  811.93     334  803.62
   343.8   793.8   353.6  785.96   363.5  781.97   373.3  781.08   412.6  781.59
   422.4   780.6   432.2  778.14   441.9  775.97   451.9  775.51   471.5   777.4
   481.4  778.26   510.8  779.46   530.5  783.17   540.3   784.3   550.1   786.6
   618.9  811.75   648.4  823.25     668  832.95   726.9  866.25   864.5  941.06
#Mann= 3 , 0 , 0
       0      .1       0   432.2    .045       0   471.5      .1       0
Bank Sta=432.2,471.5
XS Rating Curve= 0 ,0
Exp/Cntr=0.3,0.1

Type RM Length L Ch R = 1 ,22883   ,55.6,55.4,55.3
XS GIS Cut Line= 3
     1626876.902      312768.527     1626674.566      313414.457
     1626681.239      313803.457
#Sta/Elev= 30
       0 1009.72    58.9  997.38   127.5  980.64     206  954.49   264.9  941.36
   294.3   933.8   333.5  922.92   421.8  896.02   461.1  882.15   519.9  859.74
   598.4  824.71   637.6  806.24   686.6  786.87   696.3  784.63   725.5  782.53
     813  783.75     852   782.9   871.4  780.37   890.9  776.31   900.6  775.21
   905.9  776.07   910.3  776.79   929.8  784.38     959  787.06   968.7  790.88
   978.4  797.68   988.1  805.83  1036.8  848.32  1056.2  862.73  1065.9  868.09
#Mann= 3 , 0 , 0
       0     .06       0   890.9    .045       0   905.9      .1       0
Bank Sta=890.9,905.9
XS Rating Curve= 0 ,0
Exp/Cntr=0.3,0.1

Type RM Length L Ch R = 1 ,22827.6 ,602.8,585.9,571
XS GIS Cut Line= 2
     1626570.813      311505.064     1626627.926      313816.116
#Sta/Elev= 30
       0  924.78   285.3  985.32   344.3  981.76   393.5  986.45   452.5 1004.31
     541 1023.94   580.4 1030.06   609.9 1038.16   629.6 1039.79   678.8 1038.31
     787 1024.42   865.7 1002.71   914.9   991.7  1121.4  953.43  1239.5  921.33
  1347.7  906.62  1416.6   888.3  1455.9  885.67  1583.8  867.06  1721.5  841.65
  1780.6  824.42  1849.4  795.14  1878.9  786.59  1987.1  777.37  2133.1  774.77
  2134.7  774.74  2148.1   776.3  2193.7  787.52  2242.9  817.83  2311.8  844.32
#Mann= 3 , 0 , 0
       0     .06       0  2133.1    .045       0  2148.1      .1       0
Bank Sta=2133.1,2148.1
XS Rating Curve= 0 ,0
Exp/Cntr=0.3,0.1

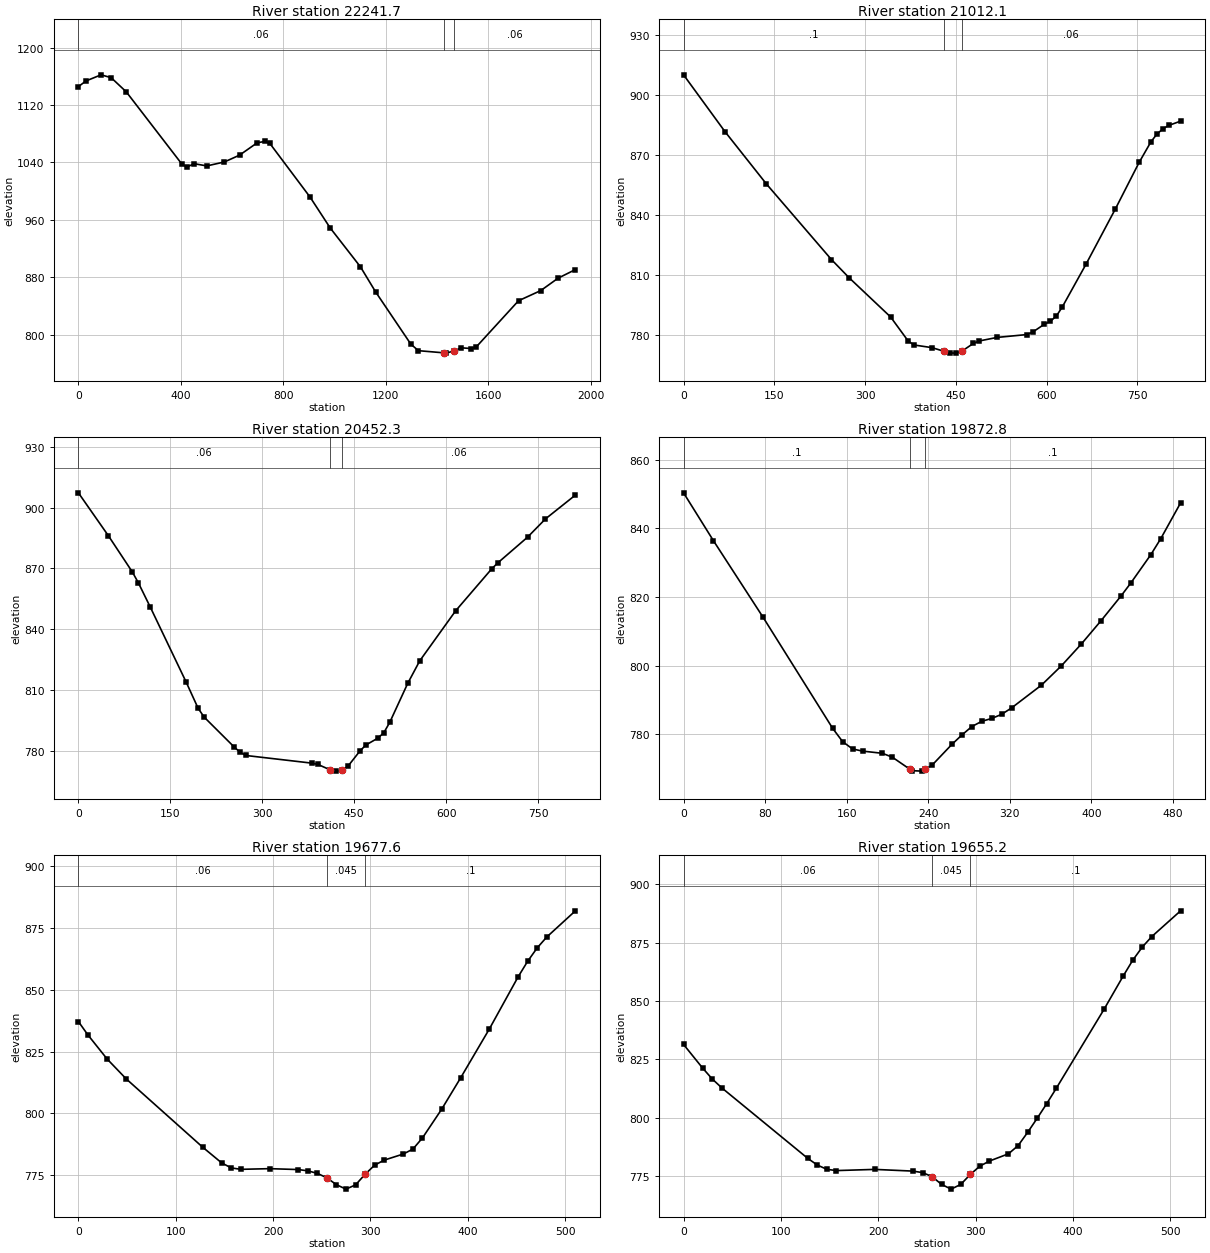
Type RM Length L Ch R = 1 ,22241.7 ,1247,1229.6,1210
XS GIS Cut Line= 4
     1624976.378      312626.374     1625990.343      313467.031
     1626107.964      313694.236     1626385.742       313933.82
#Sta/Elev= 30
       0 1145.74    29.5 1153.67    88.5 1162.22   127.8 1158.28   186.8 1138.52
     403  1038.2   422.7  1033.6   452.2 1038.31   501.3 1035.24   570.1 1040.77
   629.1 1050.28   697.9 1067.47   727.4 1069.36     747 1066.68   904.3  991.73
   982.9  948.68  1100.9  894.52  1159.9   859.7  1297.5  786.79    1327  777.66
  1425.4  774.67  1435.2  774.24  1464.7  777.09  1494.2  781.66  1533.6  780.63
  1553.3  783.04  1717.8  847.25  1804.6  861.45  1872.2  878.72  1939.8  890.72
#Mann= 3 , 0 , 0
       0     .06       0  1425.4    .045       0  1464.7     .06       0
Bank Sta=1425.4,1464.7
XS Rating Curve= 0 ,0
Exp/Cntr=0.3,0.1

Type RM Length L Ch R = 1 ,21012.1 ,556.3,559.8,563
XS GIS Cut Line= 2
     1625370.551      314460.086     1626191.298       314496.32
#Sta/Elev= 30
       0  910.21    68.5  881.75   136.9  855.58   244.5  817.69   273.8  808.55
   342.3  788.94   371.6  776.78   381.4   774.9   410.8  773.58   430.3  771.78
   440.1  770.93   449.9  770.84   459.7  771.74   479.2  775.72     489  776.94
   518.4  778.71   567.3  780.13     577  781.35   596.6  785.34   606.4  786.79
   616.2  789.38   625.9  793.86   665.1  815.26     714  843.14   753.1  866.35
   772.6  876.65   782.4   880.5   792.2  883.13     802  884.87   821.6  887.01
#Mann= 3 , 0 , 0
       0      .1       0   430.3    .045       0   459.7     .06       0
Bank Sta=430.3,459.7
XS Rating Curve= 0 ,0
Exp/Cntr=0.3,0.1

Type RM Length L Ch R = 1 ,20452.3 ,558,579.5,601
XS GIS Cut Line= 2
     1625363.607      314943.767     1626159.353      315100.486
#Sta/Elev= 30
       0  907.33    48.9  886.15    87.9   868.3    97.7  862.98   117.3   850.9
   175.9  813.82   195.4  800.89   205.2  796.56   254.1  781.82   263.8   779.2
   273.6  777.59   381.1  773.81   390.9  773.17   410.4  770.56   420.2  769.87
   430.3  770.31   439.7  772.23   459.3  779.77     469  782.75   488.6  786.15
   498.4  788.84   508.1  793.98   537.4  813.22     557  824.34   615.6  849.06
   674.2   869.7     684  872.63   732.9  885.42   762.2  894.46     811  906.22
#Mann= 3 , 0 , 0
       0     .06       0   410.4    .045       0   430.3     .06       0
Bank Sta=410.4,430.3
XS Rating Curve= 0 ,0
Exp/Cntr=0.3,0.1

Type RM Length L Ch R = 1 ,19872.8 ,196.4,195.2,194
XS GIS Cut Line= 2
     1625406.272      315264.867     1625610.265      315707.575
#Sta/Elev= 30
       0  850.37    29.2  836.45      78  814.06   146.2  781.68     156  777.79
   165.7  775.66   175.5  775.03     195  774.39   204.7  773.26     222  769.73
   224.2  769.32     234  769.19     237  769.73   243.7  770.92   263.2  777.01
     273  779.74   282.7  782.19   292.5  783.73   302.2  784.55     312  785.77
   321.7  787.63     351  794.28   370.5   799.9     390  806.24   409.4  813.06
     429  820.28   438.7   824.1   458.2  832.31     468  837.01   487.4  847.42
#Mann= 3 , 0 , 0
       0      .1       0     222    .045       0     237      .1       0
Bank Sta=222,237
XS Rating Curve= 0 ,0
Exp/Cntr=0.3,0.1

Type RM Length L Ch R = 1 ,19677.6 ,22.4,22.4,22.4
XS GIS Cut Line= 2
     1625200.277       315316.78     1625437.257      315769.036
#Sta/Elev= 30
       0  837.13     9.8   831.7    29.5  821.98    49.1  813.94   127.6  786.33
   147.3  779.91   157.1  777.91   166.9  777.34   196.4  777.61   225.8  777.25
   235.6  776.74   245.5  775.71   255.3   773.9   265.1  771.12   274.9  769.33
   284.8  771.06   294.6  775.36   304.4  779.04   314.2  781.07   333.8  783.53
   343.7  785.54   353.5  790.06   373.1  801.59   392.8  814.41   422.2  834.13
   451.7  855.18   461.5  861.48   471.3   866.9   481.1  871.29   510.6  881.92
#Mann= 3 , 0 , 0
       0     .06       0   255.3    .045       0   294.6      .1       0
Bank Sta=255.3,294.6
XS Rating Curve= 0 ,0
Exp/Cntr=0.3,0.1

Type RM Length L Ch R = 1 ,19655.2 ,279.1,287.3,295.5
XS GIS Cut Line= 2
      1625181.18      315327.196     1625418.159      315779.453
#Sta/Elev= 30
       0   831.4    19.6  821.27    29.5   816.6    39.3   812.8   127.6  782.61
   137.5  779.73   147.3  777.91   157.1  777.38   196.4  777.89   235.6  777.16
   245.5  776.52   255.3   774.8   265.1  771.46   274.9  769.44   284.8  771.47
   294.6  775.72   304.4  779.28   314.2  781.46   333.8  784.57   343.7  788.08
   353.5  793.75   363.3  799.78   373.1  806.05   382.9  812.61     432  846.46
   451.7  860.73   461.5  867.49   471.3  873.12   481.1  877.62   510.6  888.62
#Mann= 3 , 0 , 0
       0     .06       0   255.3    .045       0   294.6      .1       0
Bank Sta=255.3,294.6
XS Rating Curve= 0 ,0
Exp/Cntr=0.3,0.1

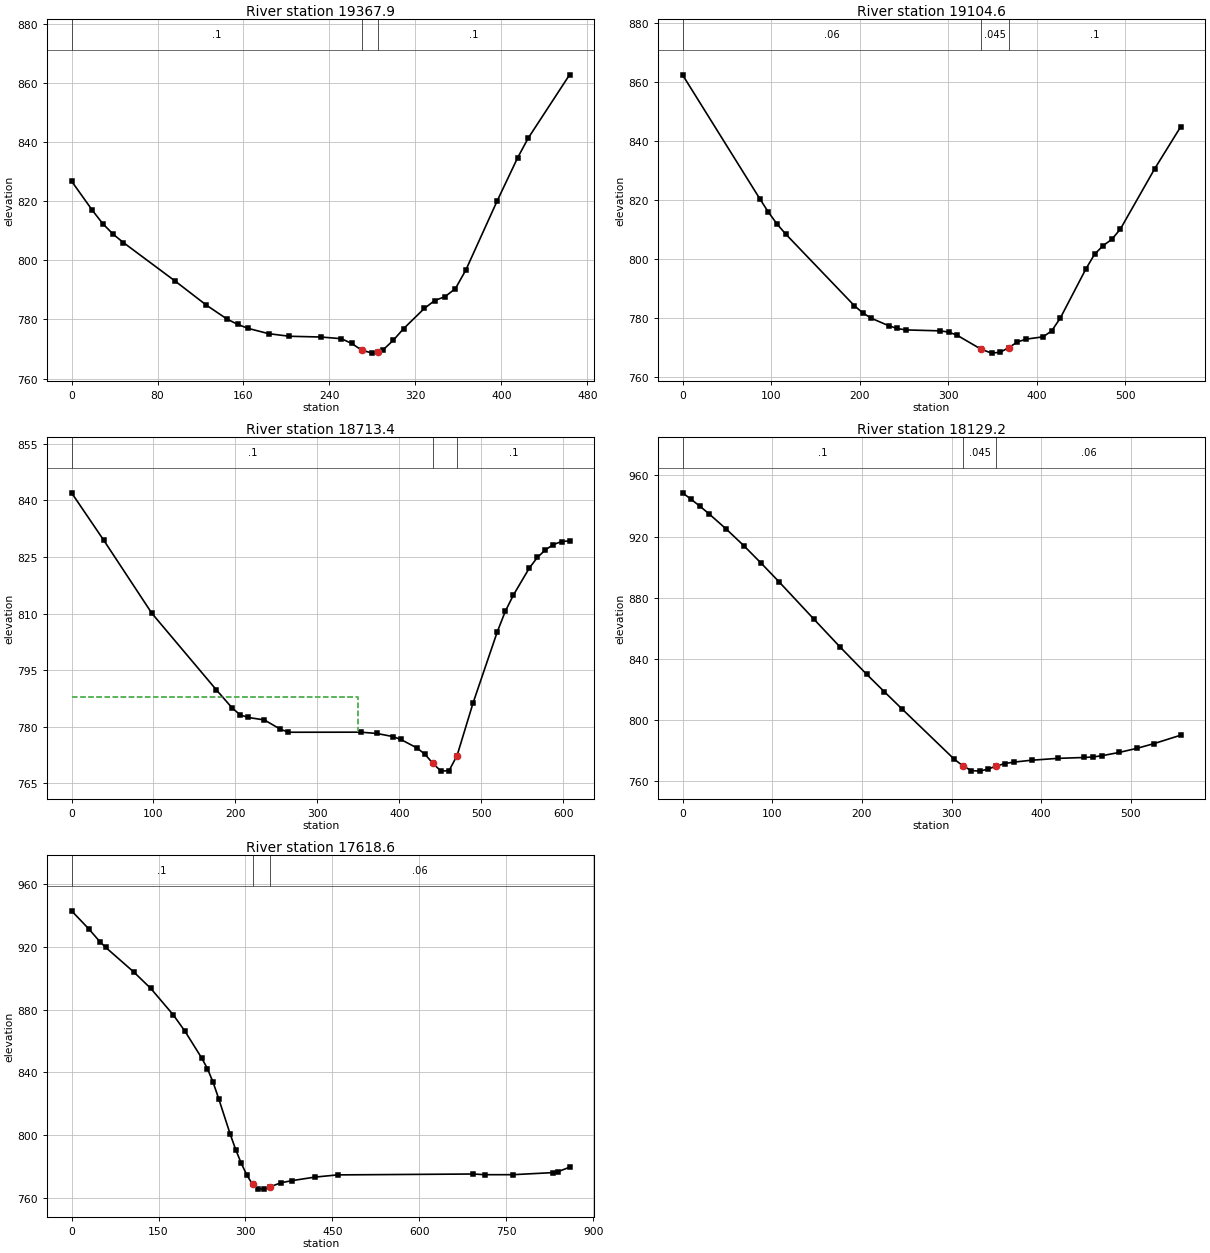
Type RM Length L Ch R = 1 ,19367.9 ,262.7,263.3,263.9
XS GIS Cut Line= 2
     1624989.605      315334.311     1625046.029      315794.381
#Sta/Elev= 30
       0  826.77    19.3  816.92      29   812.4    38.6  808.86    48.3  805.98
    96.6  792.92   125.5  784.84   144.8  780.11   154.5  778.36   164.2     777
   183.5  775.19   202.8  774.32   231.8  774.07   251.1   773.5   260.7   771.9
   270.2  769.59     280  768.62   285.2  769.17   289.7  769.64   299.4  772.95
     309  776.88   328.3  783.72     338  786.41   347.6  787.71   357.3  790.45
     367  796.74   395.9   819.9   415.2  834.69   424.9  841.24   463.5  862.71
#Mann= 3 , 0 , 0
       0      .1       0   270.2    .045       0   285.2      .1       0
Bank Sta=270.2,285.2
XS Rating Curve= 0 ,0
Exp/Cntr=0.3,0.1

Type RM Length L Ch R = 1 ,19104.6 ,388.6,391.2,393.8
XS GIS Cut Line= 2
     1624729.926      315283.697     1624780.881      315843.542
#Sta/Elev= 30
       0  862.34    87.2  820.44    96.9  815.92   106.6  811.92   116.3  808.55
   193.8  784.32   203.5  781.82   213.2  780.02   232.6  777.51   242.3  776.57
     252  776.08   290.8  775.76   300.5  775.35   310.2  774.24   336.9  769.58
   348.9  768.23   358.6  768.53   368.3  770.08     378  771.99   387.7  772.95
   407.1  773.74   416.8  775.77   426.5  780.09   455.5  796.77   465.2  801.67
   474.9  804.61   484.6  806.69   494.3  810.18   533.1  830.61   562.2  844.68
#Mann= 3 , 0 , 0
       0     .06       0   336.9    .045       0   368.3      .1       0
Bank Sta=336.9,368.3
XS Rating Curve= 0 ,0
Exp/Cntr=0.3,0.1

Type RM Length L Ch R = 1 ,18713.4 ,598.5,584.2,571.8
XS GIS Cut Line= 2
     1624403.338      315275.932     1624390.317      315883.571
#Sta/Elev= 30
       0  842.03    39.2  829.48      98  810.08   176.4  789.86   196.1  784.96
   205.9  783.13   215.7  782.46   235.3   781.8   254.9  779.34   264.7  778.54
   352.9  778.56   372.5  778.22   392.1   777.4   401.9  776.62   421.5  774.38
   431.3  772.71   441.1  770.26   450.9  768.23   460.7  768.35   470.5  772.35
   490.1  786.35   519.6  805.17   529.4  810.62   539.2  814.89   558.8  822.12
   568.6  824.91   578.4  826.92   588.2  828.32     598   829.1   607.8  829.29
#Mann= 3 , 0 , 0
       0      .1       0   441.1    .045       0   470.5      .1       0
#XS Ineff= 2 , 0
          349.67  787.82
Permanent Ineff=
       F       F
Bank Sta=441.1,470.5
XS Rating Curve= 0 ,0
Exp/Cntr=0.3,0.1

Type RM Length L Ch R = 1 ,18129.2 ,539.2,510.5,479.8
XS GIS Cut Line= 4
     1623534.353      315562.292     1623814.127      315702.534
      1623830.62      315735.781     1623992.079      315862.517
#Sta/Elev= 30
       0  948.61     9.8  944.28    19.6  939.75    29.3  935.01    48.9  924.84
    68.5  913.97      88  902.42   107.6  890.46   146.7  865.89     176  847.63
   205.4  829.95   224.9  818.65   244.5  807.48   303.2  774.35     313  769.98
   322.2  767.03   331.5  766.68   340.8  768.04   350.1  770.07   359.8  771.66
   369.6  772.58   389.2  773.81   418.5  775.02   447.8   775.6   457.6  775.95
   467.4  776.72   486.9   778.9   506.5  781.55     526  784.71   555.3  790.14
#Mann= 3 , 0 , 0
       0      .1       0     313    .045       0   350.1     .06       0
Bank Sta=313,350.1
XS Rating Curve= 0 ,0
Exp/Cntr=0.3,0.1

Type RM Length L Ch R = 1 ,17618.6 ,647.4,627.5,608.6
XS GIS Cut Line= 2
     1623247.721      316210.346     1624065.864       315947.76
#Sta/Elev= 30
       0     943    29.3  931.64    48.8  923.35    58.6  919.78   107.4  903.97
   136.7   893.5   175.8  876.52   195.3  866.43   224.6  849.11   234.3  842.47
   244.1  833.76   253.9  823.18   273.4  800.93   283.2  790.74   292.9  781.91
   302.7  774.32   312.4  768.57   322.2  765.67     332  765.56   341.8  766.96
   361.3  769.61   380.8  771.01   419.9  773.23   458.9  774.63   693.3   775.2
   712.8  774.76   761.6  774.77     830  776.08   839.7  776.77   859.2  779.51
#Mann= 3 , 0 , 0
       0      .1       0   312.4    .045       0   341.8     .06       0
Bank Sta=312.4,341.8
XS Rating Curve= 0 ,0
Exp/Cntr=0.3,0.1