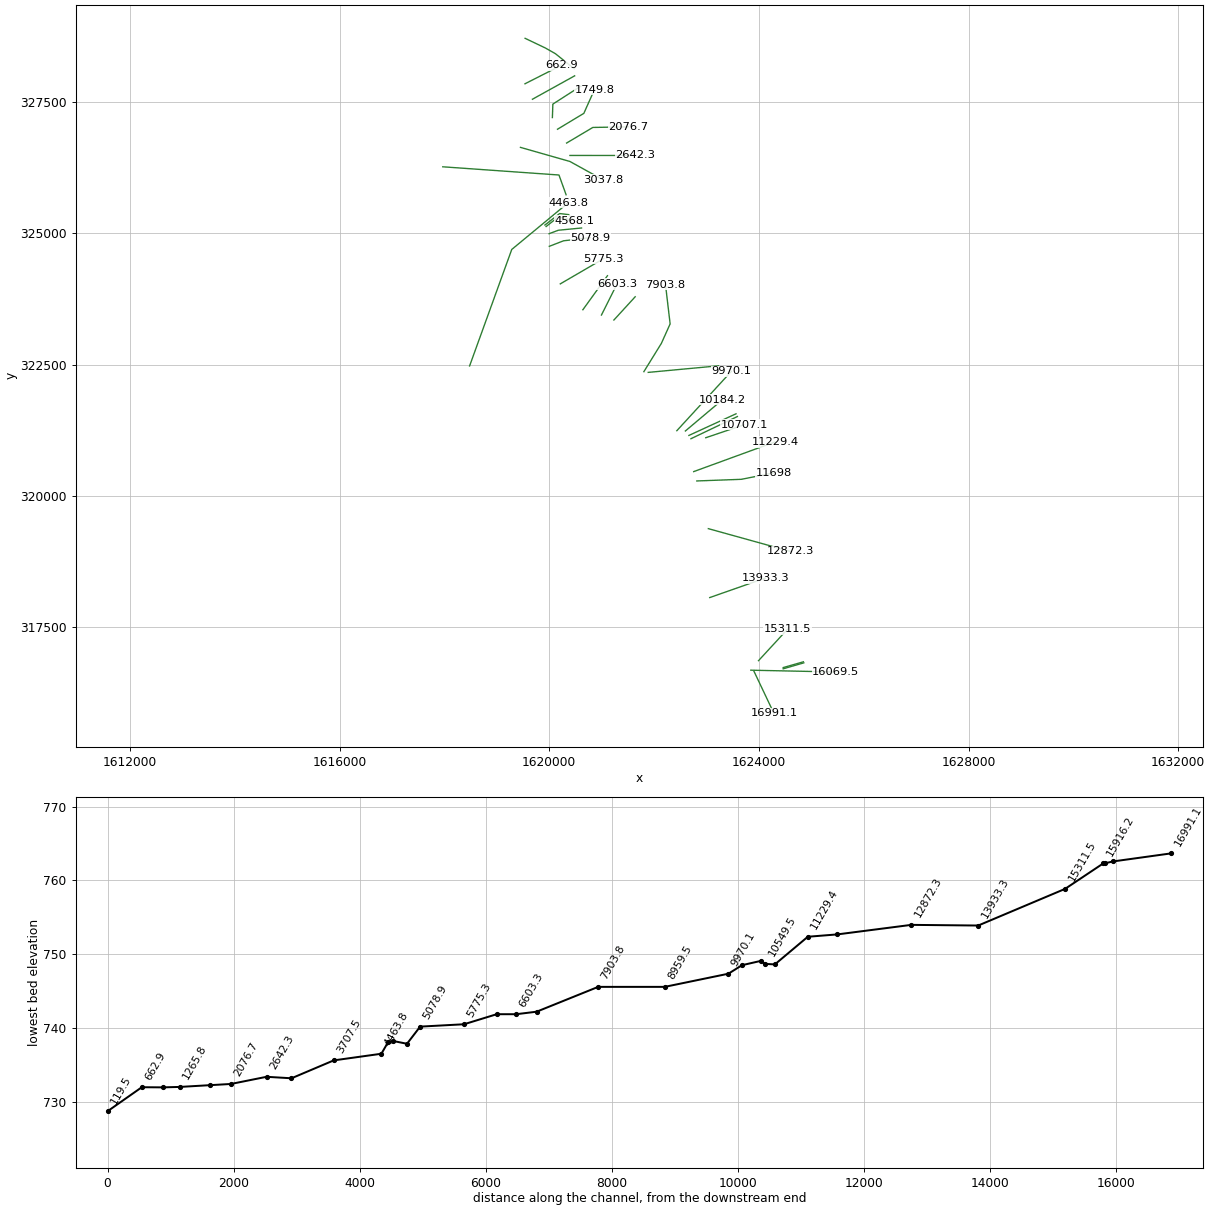
HEC-RAS study FLINTRN.prj: FLINTRN

--- FLINTRN.g01 (geometry) --- (continued)

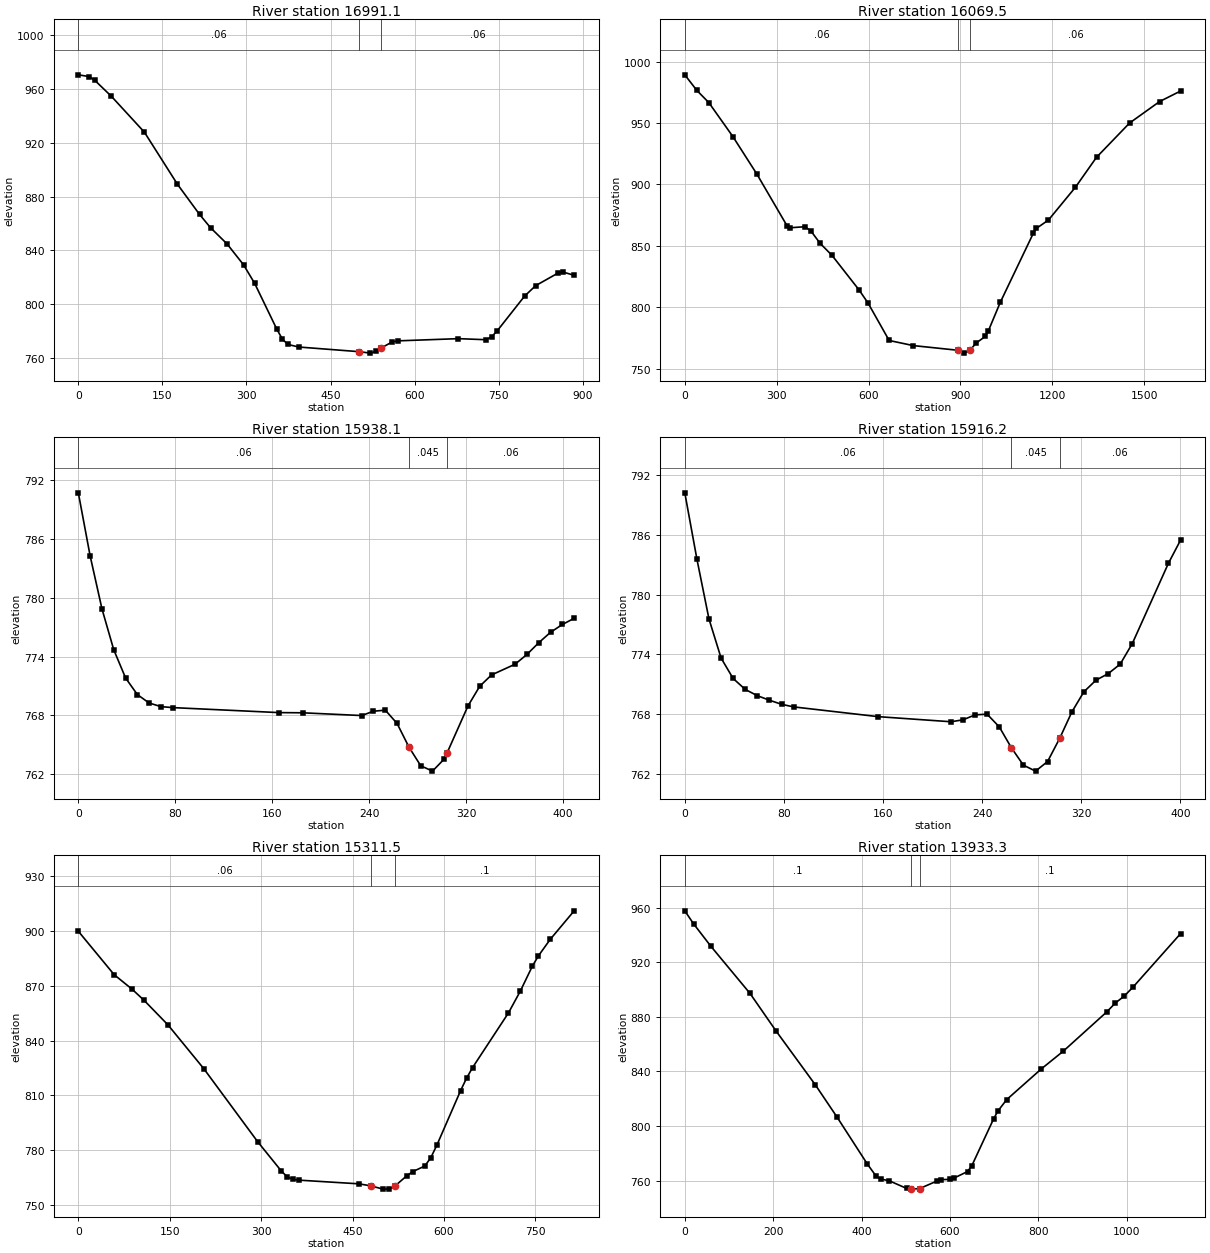
Type RM Length L Ch R = 1 ,16991.1 ,896.1,921.6,946
XS GIS Cut Line= 2
     1623907.443      316661.735     1624287.441      315862.792
#Sta/Elev= 30
       0  970.67    19.7  969.34    29.5  966.52      59  954.69     118  927.94
   176.9  889.22   216.3  866.82   235.9  856.94   265.4  844.88   294.9   829.3
   314.6  815.57   353.9  781.67   363.7  774.36   373.5  770.16   393.2  768.21
   501.3  764.73     521  763.66   530.8   764.9   540.7  767.54   560.3  772.07
   570.2  772.79   678.3  774.43   727.4  773.63   737.3  775.79   747.1  780.08
   796.2  806.04   815.9  813.82   855.2  823.04     865  823.95   884.7  821.55
#Mann= 3 , 0 , 0
       0     .06       0   501.3    .045       0   540.7     .06       0
Bank Sta=501.3,540.7
XS Rating Curve= 0 ,0
Exp/Cntr=0.3,0.1

Type RM Length L Ch R = 1 ,16069.5 ,124.5,131.4,138.2
XS GIS Cut Line= 2
     1623846.853      316684.514     1625465.603      316650.451
#Sta/Elev= 30
       0  989.34    39.2  976.69    78.5  966.69     157  939.03   235.5   908.4
   333.6  866.43   343.4  864.72   392.5  865.56   412.1  861.99   441.6  852.11
   480.8   842.2   569.1  814.04   598.6  803.28   667.3  772.87   745.8  768.72
     893  764.87   912.6  762.57   932.2  765.25   951.8  770.88   981.3  776.18
   991.1  780.63  1030.3  804.01  1138.3  860.36  1148.1  864.22  1187.4  870.98
  1275.7  897.78  1344.4  922.12  1452.3  950.04  1550.4  967.56  1619.1  976.16
#Mann= 3 , 0 , 0
       0     .06       0     893    .045       0   932.2     .06       0
Bank Sta=893,932.2
XS Rating Curve= 0 ,0
Exp/Cntr=0.3,0.1

Type RM Length L Ch R = 1 ,15938.1 ,22,21.9,21.9
XS GIS Cut Line= 2
     1624463.692      316710.876     1624856.873      316823.979
#Sta/Elev= 29
       0   790.7     9.7  784.29    19.5  778.86    29.2   774.7      39  771.81
    48.7  770.12    58.4  769.26    68.2  768.89    77.9  768.79   165.6  768.28
   185.1  768.26   233.8  767.98   243.5  768.42   253.3  768.53     263  767.17
   272.8  764.76   282.5  762.86   292.2  762.31     302  763.56   304.4  764.21
   321.5  768.96   331.2  770.97   340.9  772.12   360.4  773.22   370.2  774.22
   379.9  775.41   389.6  776.47   399.4  777.27   409.1   777.9
#Mann= 3 , 0 , 0
       0     .06       0   272.8    .045       0   304.4     .06       0
Bank Sta=272.8,304.4
XS Rating Curve= 0 ,0
Exp/Cntr=0.3,0.1

Type RM Length L Ch R = 1 ,15916.2 ,592.4,604.7,616.6
XS GIS Cut Line= 2
      1624464.17      316734.487      1624849.06      316844.161
#Sta/Elev= 29
       0   790.2     9.8  783.54    19.5  777.56    29.3  773.63      39  771.59
    48.8  770.49    58.6  769.86    68.3  769.41    78.1     769    87.8  768.74
   156.2  767.76   214.8  767.25   224.5  767.44   234.3  767.94     244  768.01
   253.8  766.74   263.6  764.64   273.3   762.9   283.1   762.3   292.8  763.26
   302.6  765.59   312.4  768.23   322.1  770.25   331.9  771.42   341.6  772.06
   351.4  773.02   361.2  775.09   390.4  783.15   400.2  785.47
#Mann= 3 , 0 , 0
       0     .06       0   263.6    .045       0   302.6     .06       0
Bank Sta=263.6,302.6
XS Rating Curve= 0 ,0
Exp/Cntr=0.3,0.1

Type RM Length L Ch R = 1 ,15311.5 ,1389.4,1378.2,1367.5
XS GIS Cut Line= 2
     1623993.206      316865.607      1624545.29      317463.523
#Sta/Elev= 30
       0  899.69    58.8  875.98    88.2  868.05   107.9  861.97   147.1  848.56
   205.9  824.65   294.2  784.82   333.4  768.67   343.2  765.45     353  764.12
   362.8  763.75   460.8  761.75   480.4  760.62   500.1  758.86   509.9  758.99
   519.7  760.57   539.3  766.21   549.1  768.46   568.7  771.48   578.5  776.03
   588.3  782.75   627.5  812.72   637.3  819.52   647.1  825.27     706  855.12
   725.6  867.11   745.2  880.64     755  886.19   774.6   895.3   813.8  910.85
#Mann= 3 , 0 , 0
       0     .06       0   480.4    .045       0   519.7      .1       0
Bank Sta=480.4,519.7
XS Rating Curve= 0 ,0
Exp/Cntr=0.3,0.1

Type RM Length L Ch R = 1 ,13933.3 ,1075.8,1061,1045.3
XS GIS Cut Line= 2
     1623062.131      318066.459     1624120.811      318436.961
#Sta/Elev= 30
       0  957.58    19.7  948.14      59  931.64   147.6   897.1   206.6  869.56
   295.2  830.26   344.4   806.6   413.2  772.12   432.9  763.34   442.8  761.33
   462.4  760.02   501.8  754.41   511.6   753.9   531.3  754.31   570.7  759.88
   580.5  760.84   600.2  761.04     610  762.16   639.5  766.75   649.4  771.12
   698.6  805.37   708.4  811.12   728.1   819.4   806.8  841.97     856  854.81
   954.4  883.57   974.1  890.16   993.7  895.09  1013.4  901.56  1121.6  940.94
#Mann= 3 , 0 , 0
       0      .1       0   511.6    .045       0   531.3      .1       0
Bank Sta=511.6,531.3
XS Rating Curve= 0 ,0
Exp/Cntr=0.3,0.1

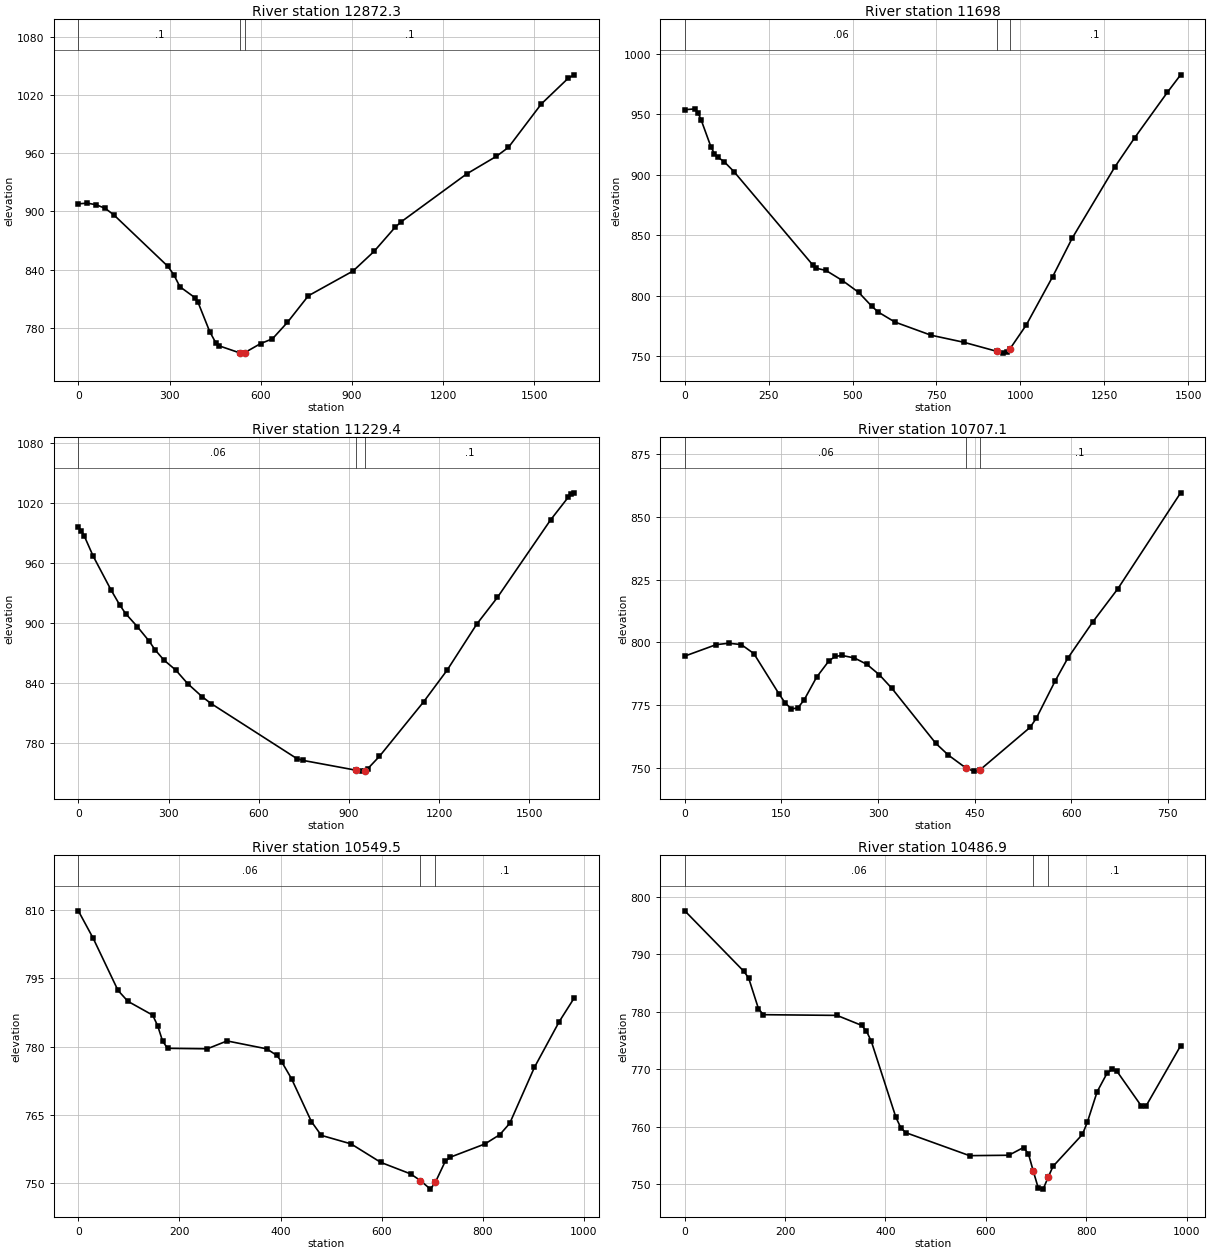
Type RM Length L Ch R = 1 ,12872.3 ,1162.6,1174.3,1185.8
XS GIS Cut Line= 2
     1623035.655      319378.351     1624607.271      318943.606
#Sta/Elev= 30
       0   907.7    29.5  908.44    58.9  906.74    88.4  903.09   117.9  896.02
   294.7  843.27   314.3  834.57     334  822.35   383.1  811.18   392.9  806.92
   432.2  776.04   451.9  764.71   461.7  761.64   532.6  754.04   540.3  753.99
   547.6  754.56   599.2  763.79   638.5  768.75   687.6  785.65   756.4  813.03
   903.7   838.6   972.5  858.73  1041.2  883.36  1060.9  889.01    1277   938.5
  1375.2  956.72  1414.5  965.86  1522.6 1010.58    1611 1037.04  1630.6 1040.56
#Mann= 3 , 0 , 0
       0      .1       0   532.6    .045       0   547.6      .1       0
Bank Sta=532.6,547.6
XS Rating Curve= 0 ,0
Exp/Cntr=0.3,0.1

Type RM Length L Ch R = 1 ,11698   ,465.1,468.6,472.1
XS GIS Cut Line= 3
     1622815.603      320285.903     1623666.298      320317.153
     1624280.881      320438.681
#Sta/Elev= 30
       0   953.7    29.4  954.36    39.1  951.37    48.9  945.14    78.3  922.73
    88.1   917.5    97.8  914.59   117.4  910.76   146.8  902.49   381.6  825.43
   391.4  822.85   420.7  820.97   469.7  812.66   518.6  802.78   557.7  791.27
   577.3  786.48   626.2  778.36   733.8   767.5   831.7  761.66   929.6  754.21
   949.2   752.7     959  753.34   968.6  755.99  1017.7  775.92    1096  815.63
  1154.7  847.66    1282  906.55  1340.7  930.48  1438.6  968.15  1477.8   982.5
#Mann= 3 , 0 , 0
       0     .06       0   929.6    .045       0   968.6      .1       0
Bank Sta=929.6,968.6
XS Rating Curve= 0 ,0
Exp/Cntr=0.3,0.1

Type RM Length L Ch R = 1 ,11229.4 ,522.9,522.3,521.8
XS GIS Cut Line= 2
     1622757.197       320463.95     1624307.008      321028.367
#Sta/Elev= 30
       0  995.95     9.8  992.26    19.6  987.19    49.1   967.1     108  933.62
   137.4  918.38   157.1  909.69   196.4  896.52   235.6   882.1   255.3  873.42
   284.7  863.24     324  853.28   363.3  839.83   412.4  826.51   441.8  819.79
   726.5  764.97   746.2  763.15     925  753.22   942.5  752.38   952.3   752.7
   962.1  754.58  1001.4  767.05  1148.7  821.57  1227.2  853.32  1325.4  899.11
  1394.1  925.74  1570.8 1003.04  1629.8 1025.77  1639.6 1028.48  1649.4 1030.14
#Mann= 3 , 0 , 0
       0     .06       0     925    .045       0   952.3      .1       0
Bank Sta=925,952.3
XS Rating Curve= 0 ,0
Exp/Cntr=0.3,0.1

Type RM Length L Ch R = 1 ,10707.1 ,154.8,157.6,160.3
XS GIS Cut Line= 2
     1622986.671      321108.224     1623715.838      321354.751
#Sta/Elev= 30
       0   794.5    48.7  799.07    68.2  799.62    87.7  799.09   107.2   795.5
   146.2  779.44   155.9  775.78   165.6  773.45   175.4  773.82   185.1  776.96
   204.6  786.09   224.1  792.71   233.8  794.35   243.6  794.77   263.1  793.78
   282.6  791.22     302  787.06   321.5  781.63   389.7   759.7   409.2  755.02
   436.6  749.85   448.2  748.64   457.9  749.06   535.9  766.06   545.6  769.67
   574.8  784.52   594.3  793.57   633.3  808.11   672.3  821.37   769.7  859.59
#Mann= 3 , 0 , 0
       0     .06       0   436.6    .045       0   457.9      .1       0
Bank Sta=436.6,457.9
XS Rating Curve= 0 ,0
Exp/Cntr=0.3,0.1

Type RM Length L Ch R = 1 ,10549.5 ,63,62.6,62.3
XS GIS Cut Line= 2
     1622704.397      321089.897     1623589.814      321511.772
#Sta/Elev= 30
       0  809.78    29.4  803.75    78.5  792.31    98.1  789.92   147.1  786.89
   156.9  784.57   166.7  781.19   176.5  779.61     255   779.5   294.2  781.23
   372.7  779.49   392.3  778.08   402.1  776.68   421.7  772.95     461  763.54
   480.6  760.51   539.4  758.64   598.3  754.58   657.1  752.06   676.7  750.59
   696.4  748.71   706.1  750.18   725.8  754.81   735.6  755.71   804.2  758.62
   833.7  760.66   853.3  763.14   902.3  775.45   951.4  785.49   980.8  790.64
#Mann= 3 , 0 , 0
       0     .06       0   676.7    .045       0   706.1      .1       0
Bank Sta=676.7,706.1
XS Rating Curve= 0 ,0
Exp/Cntr=0.3,0.1

Type RM Length L Ch R = 1 ,10486.9 ,296.6,302.7,308.7
XS GIS Cut Line= 2
     1622665.335      321152.397     1623563.772      321563.855
#Sta/Elev= 30
       0  797.59   117.4  787.08   127.2   785.9   146.8  780.55   156.5   779.5
   303.3  779.38   352.2  777.65     362  776.66   371.8  774.84   420.7  761.63
   430.5  759.81   440.3  758.96   567.5  754.95   645.7  755.02   675.1  756.37
   684.9  755.26   694.7  752.21   704.4  749.33   714.2  749.12     724  751.15
   733.8  753.08   792.5  758.65   802.3  760.78   821.8  766.08   841.4  769.28
   851.2  769.97     861  769.68   909.9   763.6   919.7  763.66   988.2  774.09
#Mann= 3 , 0 , 0
       0     .06       0   694.7    .045       0     724      .1       0
Bank Sta=694.7,724
XS Rating Curve= 0 ,0
Exp/Cntr=0.3,0.1

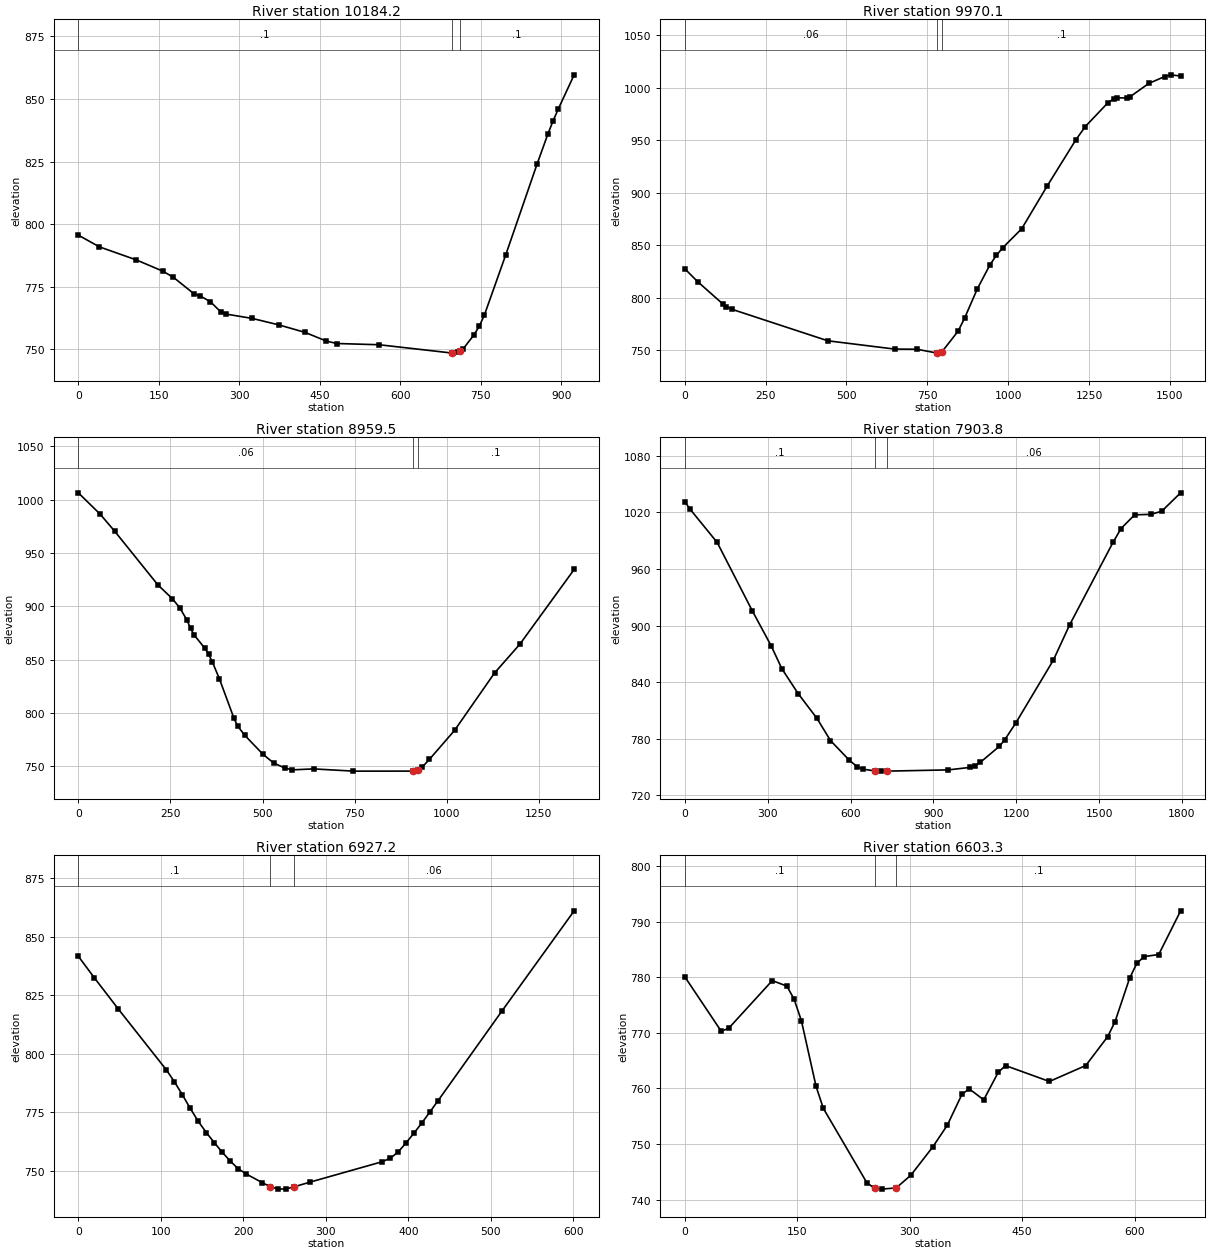
Type RM Length L Ch R = 1 ,10184.2 ,211.1,214.1,217.1
XS GIS Cut Line= 2
     1622598.112      321237.089     1623305.578      321831.707
#Sta/Elev= 30
       0  795.62    39.3  790.94   108.2  785.73   157.3  781.26     177  778.83
   216.3  772.08   226.1  771.45   245.8  769.13   265.4  765.01   275.3  764.12
   324.4  762.37   373.6  759.81   422.8  756.79   462.1  753.36   481.7  752.37
   560.4  751.88   696.7  748.56     698  748.53   707.9  748.79   711.7  749.39
   717.7  750.34   737.4  755.81   747.2   759.2     757  763.81   796.4  787.58
   855.3  824.14     875  835.84   884.8  841.19   894.7  846.03   924.2  859.61
#Mann= 3 , 0 , 0
       0      .1       0   696.7    .045       0   711.7      .1       0
Bank Sta=696.7,711.7
XS Rating Curve= 0 ,0
Exp/Cntr=0.3,0.1

Type RM Length L Ch R = 1 ,9970.1  ,1026.5,1010.6,994.2
XS GIS Cut Line= 2
     1622434.588      321242.251     1623473.408       322369.91
#Sta/Elev= 30
       0  827.71    39.3  815.57   117.9  794.12   127.8  791.66   147.4  788.96
   442.3  759.12   648.7  751.24   717.5   751.1   780.6  747.42   786.3  747.38
   795.6   748.8   845.2  768.36   864.9  780.52   904.2  808.34   943.5  831.41
   963.2  840.36   982.8  847.63  1041.8  865.82  1120.4  906.43  1208.9  950.32
  1238.4  963.12  1307.2  985.39  1326.8  989.74  1336.6  990.58  1366.1  990.25
    1376  991.33  1434.9 1004.19  1484.1 1010.78  1503.7 1012.38  1533.2 1011.17
#Mann= 3 , 0 , 0
       0     .06       0   780.6    .045       0   795.6      .1       0
Bank Sta=780.6,795.6
XS Rating Curve= 0 ,0
Exp/Cntr=0.3,0.1

Type RM Length L Ch R = 1 ,8959.5  ,1035.1,1055.7,1075.8
XS GIS Cut Line= 2
       1621889.2      322352.005     1623229.478      322477.005
#Sta/Elev= 30
       0 1006.32      59  986.42    98.3  970.52   216.2  919.98   255.5  907.06
   275.1   898.7   294.8  887.22   304.6   879.3   314.4  873.13   343.9  860.52
   353.7  854.96   363.5  848.16   383.2  831.91   422.5  795.12   432.3  787.94
     452   779.1   501.1  761.43   530.6  753.13     560   748.6   579.7  746.78
   638.7  747.69   746.7   745.6   907.8  745.61   922.8  746.45   933.4  749.26
   953.1  756.61  1021.8  783.94  1129.9  837.54  1198.7   864.5  1346.1  934.54
#Mann= 3 , 0 , 0
       0     .06       0   907.8    .045       0   922.8      .1       0
Bank Sta=907.8,922.8
XS Rating Curve= 0 ,0
Exp/Cntr=0.3,0.1

Type RM Length L Ch R = 1 ,7903.8  ,981.4,976.6,971.7
XS GIS Cut Line= 4
     1621805.808      322365.338     1622140.342       322904.93
     1622307.008      323274.721       1622218.2      324024.077
#Sta/Elev= 30
       0 1031.39    19.5 1023.26   117.2  988.13   244.2  915.72   312.6  878.51
   351.6   854.1   410.2  827.92   478.6  801.48   527.4  778.05   595.8   757.1
   625.1   750.1   644.5  747.68   688.4  745.84   712.1   745.6   731.4   745.6
   953.6  746.91  1030.8  749.48  1050.3  751.25  1069.9  754.92  1138.5   771.8
  1158.1  778.75  1197.3  796.15  1334.5  863.39  1393.3  900.75  1550.1  988.07
  1579.5  1002.9  1628.5 1017.38  1687.3 1017.95  1726.5 1021.18  1795.1 1040.74
#Mann= 3 , 0 , 0
       0      .1       0   688.4    .045       0   731.4     .06       0
Bank Sta=688.4,731.4
XS Rating Curve= 0 ,0
Exp/Cntr=0.3,0.1

Type RM Length L Ch R = 1 ,6927.2  ,317.6,323.9,330.3
XS GIS Cut Line= 2
     1621234.236      323348.651     1621640.486      323791.359
#Sta/Elev= 30
       0  841.61    19.4  832.42    48.5  819.07   106.6  793.17   116.3  788.15
     126  782.55   135.7  776.66   145.4  771.13   155.1  766.39   164.8  762.06
   174.4  757.98   184.1  754.22   193.8  750.93   203.5  748.69   222.9  745.01
   232.6  743.28   242.3  742.24     252  742.34   261.7  743.25     281  745.25
   368.3  753.94     378  755.41   387.6  758.08   397.3  762.03     407  766.24
   416.7  770.66   426.4  775.33   436.1  780.06   513.6  818.35   600.9     861
#Mann= 3 , 0 , 0
       0      .1       0   232.6    .045       0   261.7     .06       0
Bank Sta=232.6,261.7
XS Rating Curve= 0 ,0
Exp/Cntr=0.3,0.1

Type RM Length L Ch R = 1 ,6603.3  ,313.6,309.5,305.4
XS GIS Cut Line= 2
     1620996.886      323443.793     1621293.761      324034.938
#Sta/Elev= 30
       0  780.07    48.6  770.28    58.4  770.79   116.7  779.38   136.2  778.39
   145.9  776.01   155.6  772.15   175.1  760.38   184.8  756.42   243.2  742.98
   253.9  742.03   262.7   741.9   282.1  742.12   301.6   744.4   330.8  749.48
   350.2  753.38   369.7  758.93   379.4  759.93   398.8  757.95   418.3  762.93
     428   764.1   486.4  761.25     535  764.12   564.2  769.31     574     772
   593.4   779.8   603.1  782.49   612.9  783.69   632.3  784.07   661.5  791.92
#Mann= 3 , 0 , 0
       0      .1       0   253.9    .045       0   282.1      .1       0
Bank Sta=253.9,282.1
XS Rating Curve= 0 ,0
Exp/Cntr=0.3,0.1

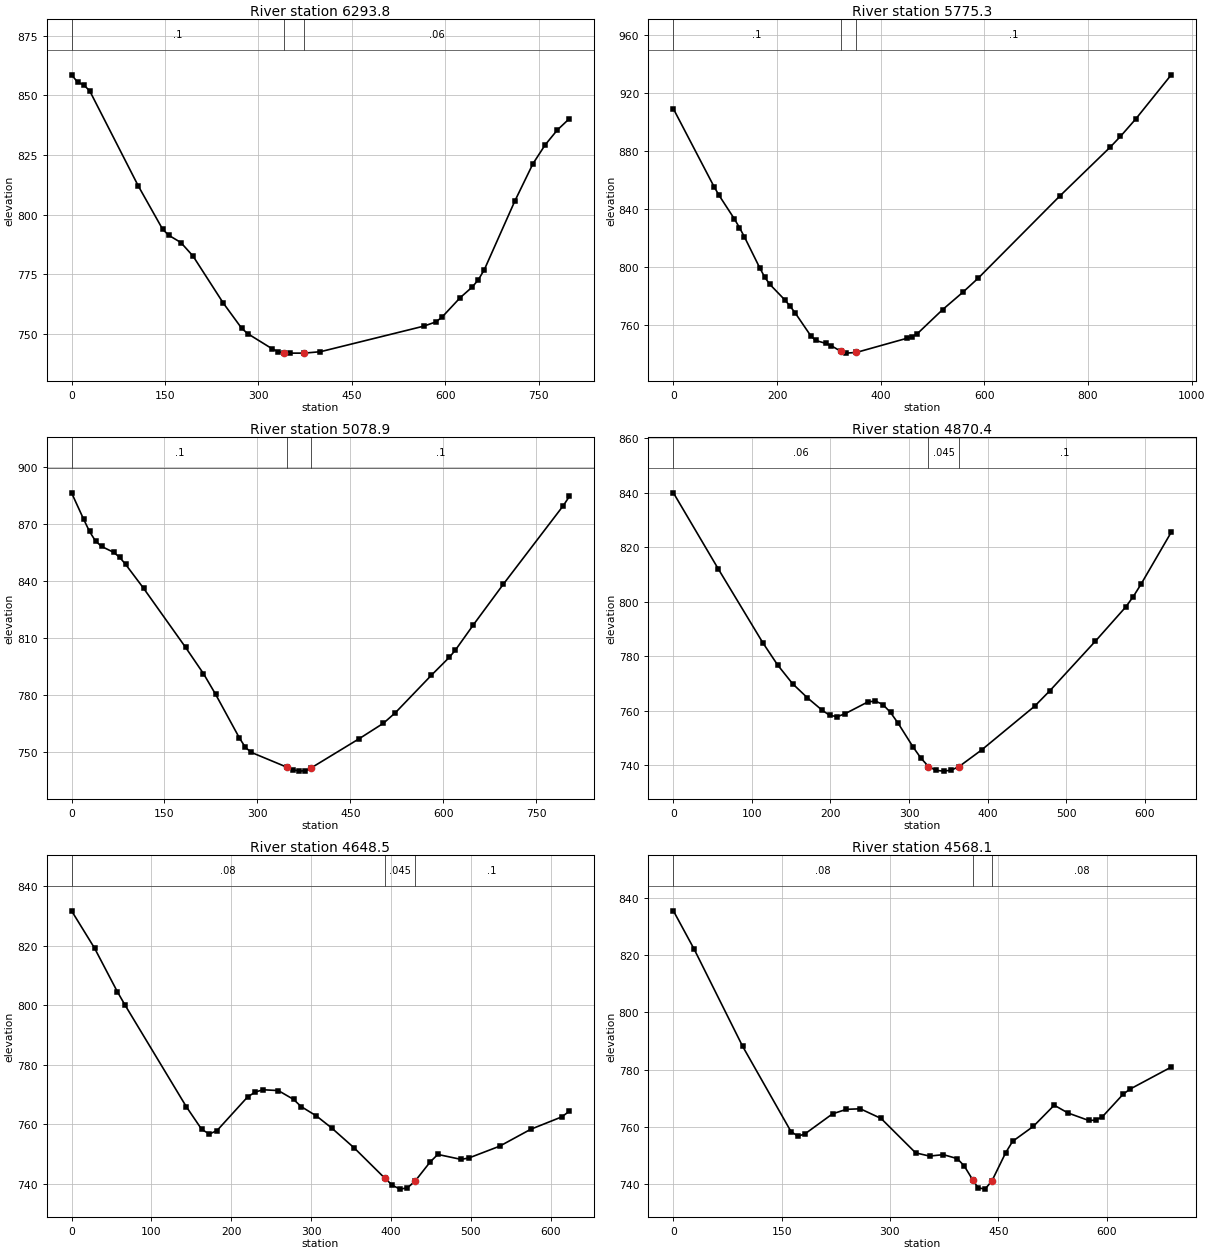
Type RM Length L Ch R = 1 ,6293.8  ,527.3,518.5,509
XS GIS Cut Line= 2
     1620642.223      323544.137     1621110.973      324191.706
#Sta/Elev= 30
       0  858.65     9.8  855.55    19.5  854.45    29.2  851.88   107.2     812
   146.2  793.89     156  791.35   175.5   788.3     195  782.63   243.7  762.86
     273  752.38   282.7  750.09   321.7  743.78   331.5   742.5   341.2  741.93
     351   741.9   373.7   741.9   399.7   742.5   565.4  753.21   584.9  754.98
   594.7  756.96   623.9  765.13   643.4  769.64   653.2  772.69   662.9  776.98
   711.7  805.67   740.9  821.38   760.4  829.24   779.9  835.48   799.4  840.28
#Mann= 3 , 0 , 0
       0      .1       0   341.2    .045       0   373.7     .06       0
Bank Sta=341.2,373.7
XS Rating Curve= 0 ,0
Exp/Cntr=0.3,0.1

Type RM Length L Ch R = 1 ,5775.3  ,705.4,696.4,687
XS GIS Cut Line= 2
     1620211.233      324036.324     1621041.919      324518.811
#Sta/Elev= 30
       0   909.1    78.4  855.41    88.2  849.36   117.6  833.17   127.4  827.19
   137.2  820.64   166.6  799.38   176.4  792.85   186.2  787.95   215.6  777.04
   225.5  772.78   235.3  768.12   264.7  752.69   274.5  749.28   294.1  747.26
   303.9   745.8   323.5  741.71   333.3  740.54   352.9     741   450.9  750.82
   460.7  751.91   470.5  753.89   519.5  770.56   558.7  782.59   588.2  792.28
     745  848.72     843   882.7   862.6  890.06     892  902.02   960.6  932.54
#Mann= 3 , 0 , 0
       0      .1       0   323.5    .045       0   352.9      .1       0
Bank Sta=323.5,352.9
XS Rating Curve= 0 ,0
Exp/Cntr=0.3,0.1

Type RM Length L Ch R = 1 ,5078.9  ,209,208.5,208
XS GIS Cut Line= 3
     1620001.598      324751.168      1620272.55      324855.823
     1620782.359      324916.109
#Sta/Elev= 30
       0  886.23    19.4  872.44      29  865.96    38.7  860.92    48.4  858.12
    67.8  855.03    77.5  852.45    87.1  848.77   116.2  836.19     184  805.19
     213  791.36   232.4  780.62   271.1  757.55   280.8  752.62   290.5  750.01
   348.6  742.16   358.3  740.86     368  740.22   377.6  740.46   387.3     742
   464.8  757.32   503.6  765.36   522.9   770.9     581  790.55   610.1     800
   619.8  803.77   648.8     817   697.3  838.37   794.1  879.58   803.8  884.39
#Mann= 3 , 0 , 0
       0      .1       0   348.6    .045       0   387.3      .1       0
Bank Sta=348.6,387.3
XS Rating Curve= 0 ,0
Exp/Cntr=0.3,0.1

Type RM Length L Ch R = 1 ,4870.4  ,227,221.9,216.6
XS GIS Cut Line= 3
     1619996.886      324990.668     1620174.403      325057.291
     1620616.678      325100.043
#Sta/Elev= 30
       0  839.91    56.9  812.14   113.8  784.99   132.7  776.82   151.7  769.96
   170.6  764.79   189.6  760.18   199.3  758.31   208.9  757.88   218.6  758.94
   247.6  763.26   257.2  763.59   266.9  762.29   276.5  759.39   286.2  755.43
   305.5  746.61   315.2  742.66   324.8  739.59   334.5  738.17   344.2   737.9
   353.8  738.26   363.5  739.52   392.5  745.67   460.1  761.73   479.4  767.38
   537.4  785.56     576  798.08   585.6  801.89   595.3  806.36   633.9  825.48
#Mann= 3 , 0 , 0
       0     .06       0   324.8    .045       0   363.5      .1       0
Bank Sta=324.8,363.5
XS Rating Curve= 0 ,0
Exp/Cntr=0.3,0.1

Type RM Length L Ch R = 1 ,4648.5  ,81.7,80.3,78.4
XS GIS Cut Line= 4
     1619940.856      325127.723     1620167.299      325305.077
     1620337.271      325285.417     1620446.064      325161.577
#Sta/Elev= 30
       0  831.72    28.8  819.19    57.5  804.49    67.1  800.02   143.8  765.93
     163  758.35   172.6  756.77   182.2  757.94   220.5  769.23   230.1  770.87
   239.7  771.64   258.9  771.38     278  768.42   287.6  765.99   306.6  762.87
   325.6  758.86   354.2  752.07   392.2     742   401.7  739.62   411.2  738.28
   420.7  738.71   430.2  740.94   449.2   747.4   458.7  749.93   487.8  748.27
   497.5  748.72   536.3  752.71   575.1  758.37   613.9  762.52   623.6  764.44
#Mann= 3 , 0 , 0
       0     .08       0   392.2    .045       0   430.2      .1       0
Bank Sta=392.2,430.2
XS Rating Curve= 0 ,0
Exp/Cntr=0.3,0.1

Type RM Length L Ch R = 1 ,4568.1  ,84.3,104.3,124.8
XS GIS Cut Line= 4
     1619918.721      325156.368     1620198.457      325374.588
     1620370.041      325354.741     1620477.314      325233.191
#Sta/Elev= 30
       0  835.61    28.8  822.15    95.9  788.14     163  758.22   172.6  756.65
   182.2  757.44   220.5  764.48   239.7  766.05   258.9  766.24   287.7  762.85
   335.6  750.79   354.8  749.67     374  750.17   393.2  748.78   402.8  746.24
   414.9  741.22     422  738.59   431.6  738.09   441.2  740.96   460.3  750.85
   469.9  754.84   498.7  760.11   527.5   767.5   546.6  764.77   575.2  762.16
   584.7  762.26   594.3  763.47   622.9  771.33   632.4  773.12   689.6  780.86
#Mann= 3 , 0 , 0
       0     .08       0   414.9    .045       0   441.2     .08       0
Bank Sta=414.9,441.2
XS Rating Curve= 0 ,0
Exp/Cntr=0.3,0.1

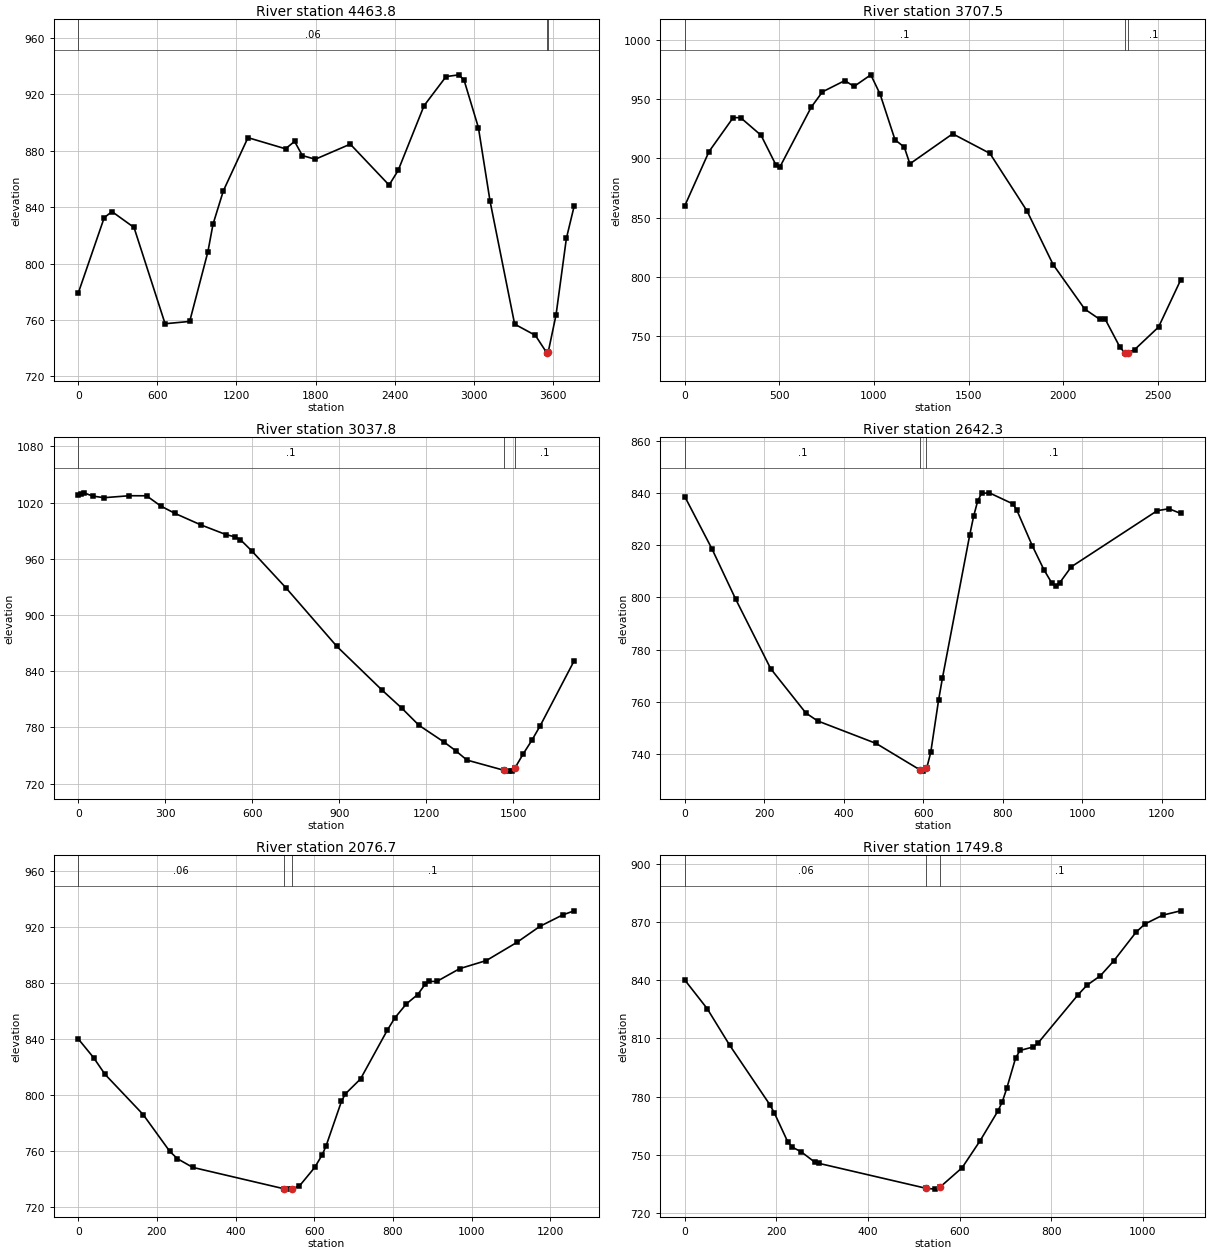
Type RM Length L Ch R = 1 ,4463.8  ,800.4,756.4,711.8
XS GIS Cut Line= 3
     1618481.264      322474.737     1619285.325      324691.324
     1620368.308      325584.783
#Sta/Elev= 30
       0  779.25   196.5  832.54   255.4  836.79   422.5  825.56   658.2  757.37
   844.9     759   982.5  808.12  1021.8  827.85  1100.4  851.54    1287  889.18
  1571.9  881.28  1640.7  886.52  1699.7  876.49  1797.9  873.89  2063.2  884.58
  2357.9  855.58  2426.6  865.99    2623   911.8  2789.9  932.43  2888.1  933.68
  2927.4  929.67  3035.4  896.31  3123.7  844.23  3310.3  757.09  3467.3  749.16
  3555.7  736.55  3565.5  737.48  3624.4  763.62    3703  817.87  3761.9  840.68
#Mann= 3 , 0 , 0
       0     .06       0  3555.7    .045       0  3565.5      .1       0
Bank Sta=3555.7,3565.5
XS Rating Curve= 0 ,0
Exp/Cntr=0.3,0.1

Type RM Length L Ch R = 1 ,3707.5  ,652.8,669.7,685.9
XS GIS Cut Line= 3
     1617970.011      326264.594     1620186.448      326108.318
     1620321.864      325733.318
#Sta/Elev= 30
       0     860   127.8  905.65   255.6  934.34     295  934.32   403.1  919.44
   481.8  894.36   501.4  892.32   668.6  943.27   727.5   956.1   845.5  965.57
   894.7  960.69   983.2  970.46  1032.3  954.11    1111  915.66  1160.1  909.45
  1189.6  895.36  1415.8   920.7  1612.4   904.2    1809   855.5  1946.6   810.4
  2113.8   772.8  2192.4  764.26  2221.9  764.29  2299.7  740.71  2325.1  735.92
  2328.9  735.65  2340.1  735.86  2377.5  738.62    2504  757.67  2620.6  797.28
#Mann= 3 , 0 , 0
       0      .1       0  2325.1    .045       0  2340.1      .1       0
Bank Sta=2325.1,2340.1
XS Rating Curve= 0 ,0
Exp/Cntr=0.3,0.1

Type RM Length L Ch R = 1 ,3037.8  ,384,395.5,406.8
XS GIS Cut Line= 3
     1619451.793      326634.168     1620394.372      326366.191
     1621033.661       326014.33
#Sta/Elev= 30
       0 1027.82     9.8 1029.61    19.6 1030.39      49 1026.96    88.2 1025.19
   176.4 1027.29   235.2 1027.23   284.2 1016.32   333.2 1008.42   421.4  996.31
   509.6  985.73     539  983.48   558.6  980.45   597.8  968.43   715.4  929.12
   891.7  866.35    1048  819.53  1116.2  800.22  1174.5  782.19  1262.1  764.03
    1301  755.08  1339.9  745.04  1466.4  734.24  1485.9  733.23  1495.6  733.77
  1505.3  736.46  1534.5  751.89  1563.7  766.07  1592.9  781.84  1709.7  851.03
#Mann= 3 , 0 , 0
       0      .1       0  1466.4    .045       0  1505.3      .1       0
Bank Sta=1466.4,1505.3
XS Rating Curve= 0 ,0
Exp/Cntr=0.3,0.1

Type RM Length L Ch R = 1 ,2642.3  ,553.3,565.7,577.9
XS GIS Cut Line= 2
     1620395.641      326480.441      1621643.73      326480.064
#Sta/Elev= 30
       0  838.64    68.8  818.48   127.8  799.42   216.2  772.69   304.6  755.73
   334.1  752.69   481.6  744.04   592.2  733.89   599.5  733.43   607.2   734.5
   609.3  734.79   619.1  740.62   638.8  760.63   648.6  769.17   717.4  824.08
   727.2   831.2   737.1  836.88   746.9  839.86   766.5  840.09   825.5  835.88
   835.3  833.64   874.6  819.84   904.1  810.58   923.8  805.52   933.6  804.41
   943.4  805.55   972.9  811.74  1189.1  833.24  1218.6     834  1248.1   832.2
#Mann= 3 , 0 , 0
       0      .1       0   592.2    .045       0   607.2      .1       0
Bank Sta=592.2,607.2
XS Rating Curve= 0 ,0
Exp/Cntr=0.3,0.1

Type RM Length L Ch R = 1 ,2076.7  ,326.3,326.8,327.8
XS GIS Cut Line= 3
     1620332.187      326716.855     1620832.609      327013.472
     1621511.689      327024.793
#Sta/Elev= 30
       0     840    38.8  826.64    67.9  814.67   164.8  785.89   232.7  759.44
   252.1  754.23   290.9  748.04   523.6  732.67   533.2  732.46   542.9  732.71
   562.3  734.73   601.1  747.99   620.5   757.2   630.2  763.56     669  795.23
   678.8  800.61   717.6  811.38   785.5  846.18   804.9  855.11     834  865.08
   863.1  871.86   882.5  879.39   892.2  881.22   911.6  881.23   969.8  890.38
  1037.7   896.2  1115.4  909.22  1173.6  920.65  1231.8  928.88  1260.9   931.8
#Mann= 3 , 0 , 0
       0     .06       0   523.6    .045       0   542.9      .1       0
Bank Sta=523.6,542.9
XS Rating Curve= 0 ,0
Exp/Cntr=0.3,0.1

Type RM Length L Ch R = 1 ,1749.8  ,484.4,484.1,483.4
XS GIS Cut Line= 3
     1620158.434      326979.531     1620660.734      327281.701
     1620863.859      327734.826
#Sta/Elev= 30
       0     840    48.8  825.29    97.7  806.53   185.6  775.83   195.4  771.63
   224.7  756.72   234.5  753.92     254  751.56   283.3  746.29   293.1  745.56
   527.6  732.69   547.1   732.3   556.9  733.24   605.7  743.35   644.6  757.11
   683.6  772.45   693.3  777.24     703  784.14   722.5   799.9   732.2  803.74
   761.4  805.55   771.2  807.48   858.8  832.41   878.3  837.33   907.5  842.19
   936.7  849.82   985.4  864.61  1004.9  868.87  1043.8  873.42  1082.8  875.64
#Mann= 3 , 0 , 0
       0     .06       0   527.6    .045       0   556.9      .1       0
Bank Sta=527.6,556.9
XS Rating Curve= 0 ,0
Exp/Cntr=0.3,0.1

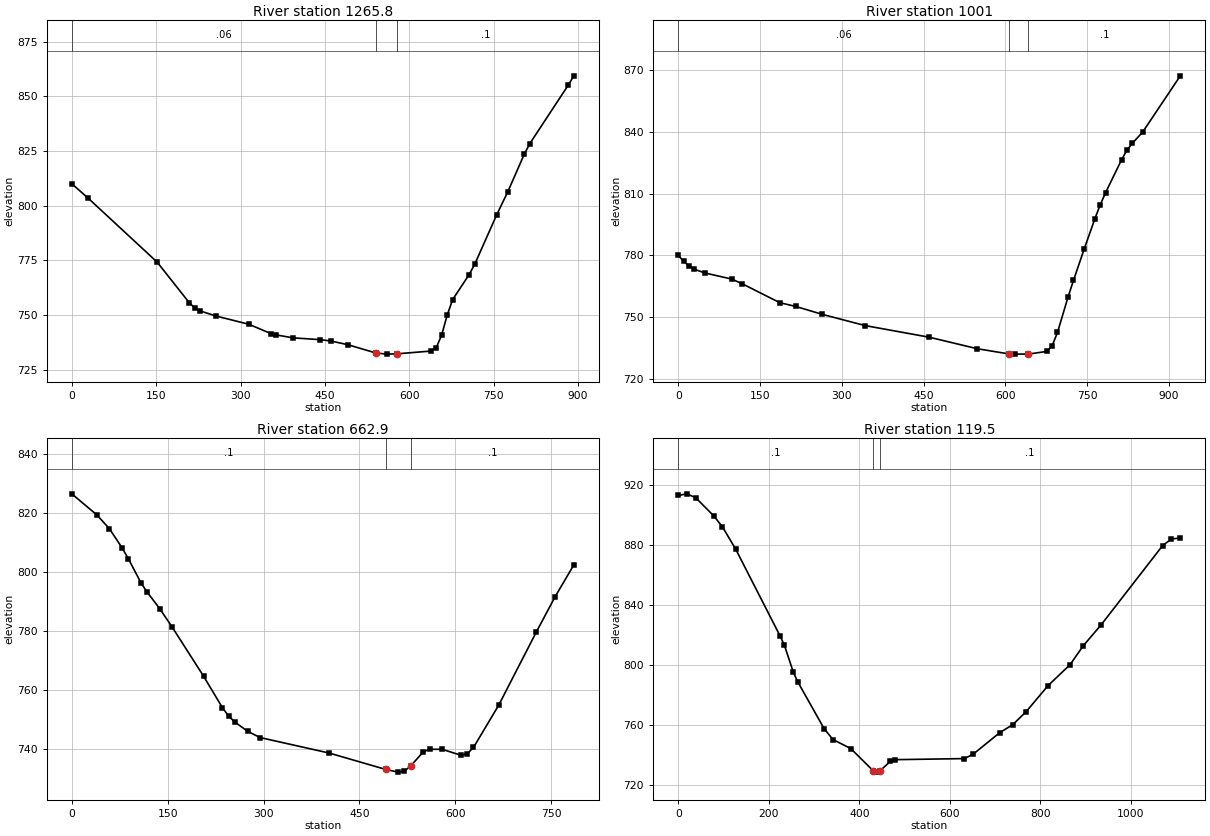
Type RM Length L Ch R = 1 ,1265.8  ,265.8,264.7,263.7
XS GIS Cut Line= 3
     1620060.701      327201.805     1620069.588      327457.743
     1620605.425      327801.199
#Sta/Elev= 30
       0     810    28.4  803.56   151.8  774.14   208.7  755.63   218.2  753.26
   227.6  751.87   256.1  749.51   314.8  745.72     354  741.46   363.8  740.84
   393.2   739.5   442.1  738.68   461.7  738.01   491.1  736.35     540  732.63
   559.6  732.06   577.7  732.19     638  733.45   647.8  734.92   657.6  740.75
   667.3  749.79   677.1     757   706.5  768.45   716.3  773.12   755.5  795.82
     775  806.22   804.4  823.47   814.2  828.31   882.8  855.15   892.6  859.35
#Mann= 3 , 0 , 0
       0     .06       0     540    .045       0   577.7      .1       0
Bank Sta=540,577.7
XS Rating Curve= 0 ,0
Exp/Cntr=0.3,0.1

Type RM Length L Ch R = 1 ,1001    ,339.3,338.1,336.8
XS GIS Cut Line= 2
     1619680.075       327550.39     1620485.803      327995.724
#Sta/Elev= 30
       0     780     9.8  777.15    19.6  774.91    29.4  773.27      49  771.44
    97.9   768.5   117.5  766.18   186.1  757.02   215.5  755.18   264.4  751.31
   342.8  745.87   460.3  740.22   548.4  734.62   607.2  732.06     617     732
     642  732.03   675.8  733.31   685.6  736.04   695.4  742.57   714.9  759.88
   724.7  767.84   744.3  783.05   763.9  797.79   773.7  804.55   783.5  810.45
   812.9  826.51   822.7  831.12   832.5  834.43     852  840.11   920.6  867.29
#Mann= 3 , 0 , 0
       0     .06       0   607.2    .045       0     642      .1       0
Bank Sta=607.2,642
XS Rating Curve= 0 ,0
Exp/Cntr=0.3,0.1

Type RM Length L Ch R = 1 ,662.9   ,563.4,543.3,520.6
XS GIS Cut Line= 2
     1619538.338      327844.722     1620239.105      328199.462
#Sta/Elev= 30
       0   826.4    39.3  819.24    58.9  814.56    78.5  808.15    88.4  804.44
     108  796.31   117.8  793.09   137.4  787.51   157.1  781.19   206.2  764.54
   235.6   753.9   245.4  751.02   255.3  748.97   274.9   745.9   294.5  743.75
   402.5   738.5   490.9  732.95   510.5  732.02   520.4  732.37   530.2  734.11
   549.8  738.88   559.6  739.77   579.3  739.76   608.7  737.76   618.5  738.19
   628.4  740.38   667.6  754.62   726.5  779.46     756  791.48   785.4   802.3
#Mann= 3 , 0 , 0
       0      .1       0   490.9    .045       0   530.2      .1       0
Bank Sta=490.9,530.2
XS Rating Curve= 0 ,0
Exp/Cntr=0.3,0.1

Type RM Length L Ch R = 1 ,119.5   ,129.1,119.5,111.1
XS GIS Cut Line= 4
     1619540.943      328709.305     1619928.963       328524.41
     1620121.672      328415.035     1620478.443      328128.576
#Sta/Elev= 30
       0  912.92    19.5  914.02    39.1  911.27    78.2  899.44    97.7  892.03
     127  877.13   224.7  819.56   234.4  813.32     254  795.48   263.8  788.98
   322.4  757.61   341.9  750.44     381  744.47   430.5  729.73   439.5  728.77
   445.5  729.63   468.4  735.87     478  737.06   632.1  737.78   651.4   740.7
   709.8  754.96     739  760.39   768.2  768.91   816.9  786.36   865.6  800.34
   894.8  812.93   933.7  826.66    1070  879.59  1089.5  883.97    1109  884.63
#Mann= 3 , 0 , 0
       0      .1       0   430.5    .045       0   445.5      .1       0
Bank Sta=430.5,445.5
XS Rating Curve= 0 ,0
Exp/Cntr=0.3,0.1

Chan Stop Cuts=-1
Use User Specified Reach Order=0
Composite Channel Slope=5